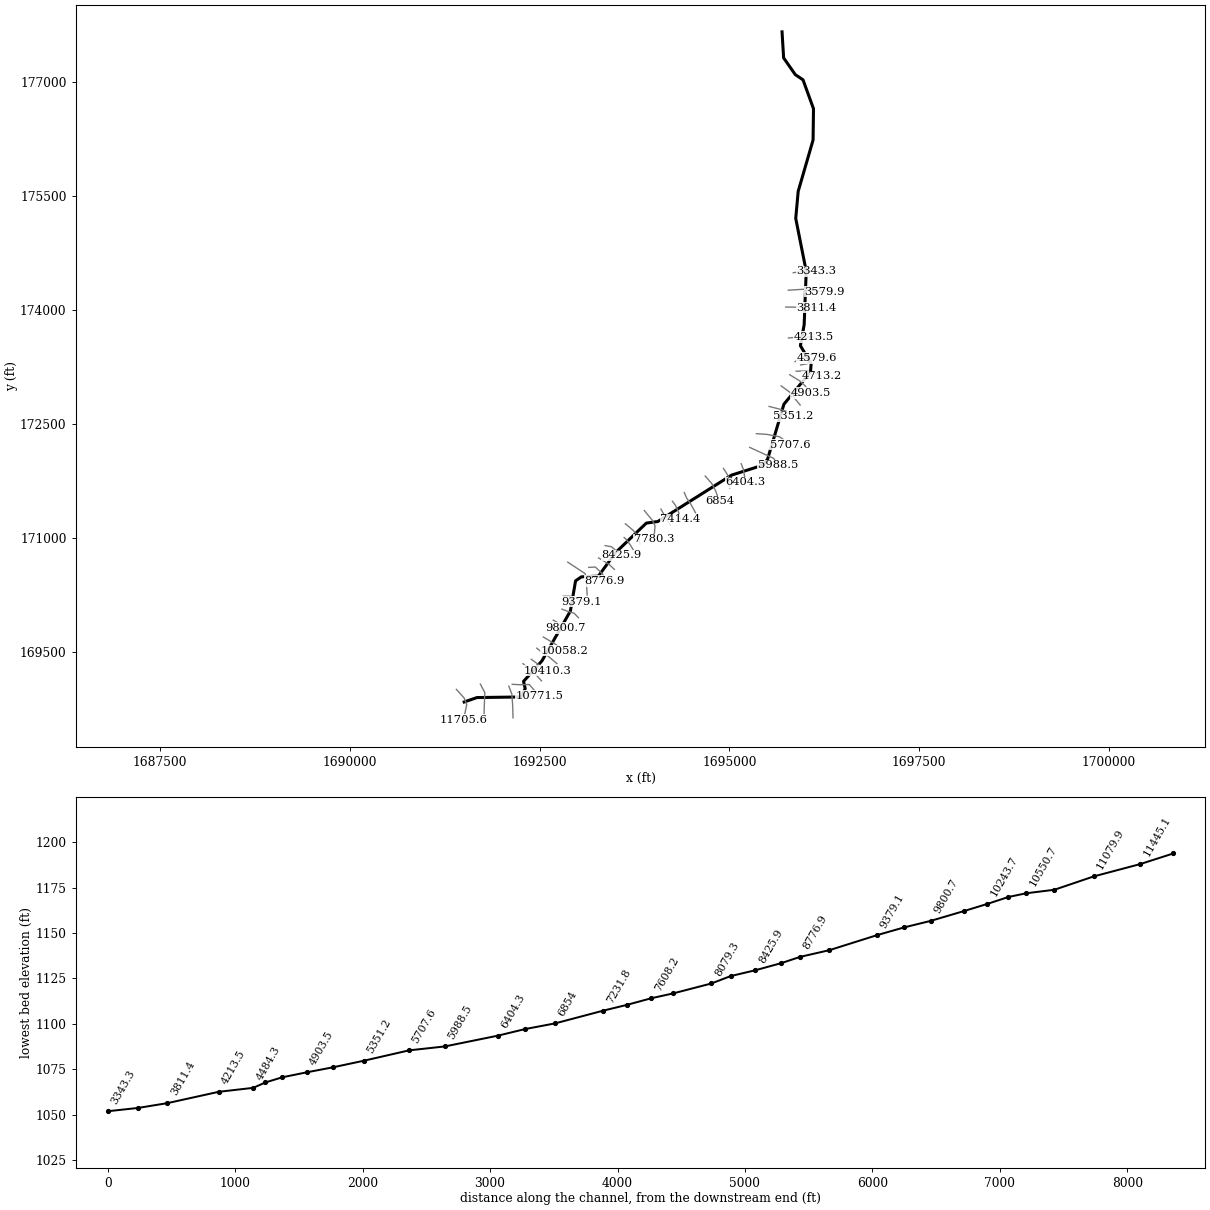
--- Mud Fork.prj (project) ---

Proj Title=Mud Fork
Current Plan=p01
Default Exp/Contr=0,0
English Units
Geom File=g01
Flow File=f01
Plan File=p01
BEGIN DESCRIPTION:
END DESCRIPTION:
DSS Export Rating Curves= 0
DSS Export Rating Curve Sorted= 0
DSS Export Volume Flow Curves= 0
DXF OffsetX= 0
DXF OffsetY= 0
DXF ScaleX= 0
DXF ScaleY= 0

--- Mud Fork.p01 (plan) ---

Plan Title=Floodplain
Program Version=4.00
Geom File=g01
Flow File=f01
K Sum by GR=0
Std Step Tol=0.01
Critical Tol=0.01
Num of Std Step Trials=20
Max Error Tol=0.3
Flow Tol Ratio=0.001
Split Flow NTrial=30
Split Flow Tol=0.02
Split Flow Ratio=0.02
Log Output Level=0
Friction Slope Method=1
Unsteady Friction Slope Method=2
Unsteady Bridges Friction Slope Method=1
Global Log Level=0
CheckData=False
Run HTab=0
Run UNet=0
Run PostProcess=0
UNET Theta=0
UNET Theta Warmup=0
UNET ZTol=0
UNET ZSATol=0
UNET MxIter=0
UNET MaxInSteps=0
UNET DtIC=0
UNET DtMin=0
UNET MaxCRTS=0
UNET WFStab=0
UNET SFStab=0
UNET WFX=0
UNET SFX=0
UNET DSS MLevel=0
UNET DZMax Abort=0
UNET Convert EG Bridges=0
UNET Use Existing IB Tables=0
UNET Froude Limit=0
UNET Froude Power=0
Write IC File=0
Echo Input=False
Echo Output=False
Write Detailed=0

--- Mud Fork.f01 (steady flow) ---

Flow Title=NFF Regression Equation
Program Version=4.00
Number of Profiles=1
Profile Names=P100yr
River Rch & RM=Mud Fork,Main      ,11705.6
581.4082
River Rch & RM=Mud Fork,Main      ,11079.9
590.3472
River Rch & RM=Mud Fork,Main      ,10771.5
808.8806
River Rch & RM=Mud Fork,Main      ,8230.6
875.4328
River Rch & RM=Mud Fork,Main      ,7780.3
965.5975
River Rch & RM=Mud Fork,Main      ,5988.5
1037.732
River Rch & RM=Mud Fork,Main      ,4484.3
1137.025
River Rch & RM=Mud Fork,Main      ,2990.5
1189.505
River Rch & RM=Mud Fork,Main      ,299.4
1303.631
Boundary for River Rch & Prof#=Mud Fork,Main      ,1
Up Type=0
Dn Type=3
Dn Slope=0.016416

--- Mud Fork.g01 (geometry) ---

Geom Title=Geometry
Program Version=4.00

River Reach=Mud Fork        ,Main
Reach XY= 30
     1691508.746      168840.999     1691676.811      168898.823
     1692258.189      168906.619     1692311.649      169016.324
     1692289.931      169112.106     1692531.615      169381.077
     1692906.392      170037.633     1692974.887      170435.799
     1693051.736      170488.145       1693275.6      170497.612
      1693498.35       170804.45      1693906.54      171195.933
     1694057.453      171216.538     1695026.972      171826.873
     1695431.732      171955.623     1695501.987      172035.144
     1695718.055      172761.309     1696067.456      173185.384
     1696076.126      173292.569     1695934.679      173532.025
     1695984.241      173806.564     1696011.528      174511.011
     1695873.423      175207.662     1695905.722      175563.506
     1696101.742      176239.552      1696107.31       176651.64
     1695969.205      177031.985     1695867.297      177100.481
     1695714.156      177320.447      1695693.11      177663.339

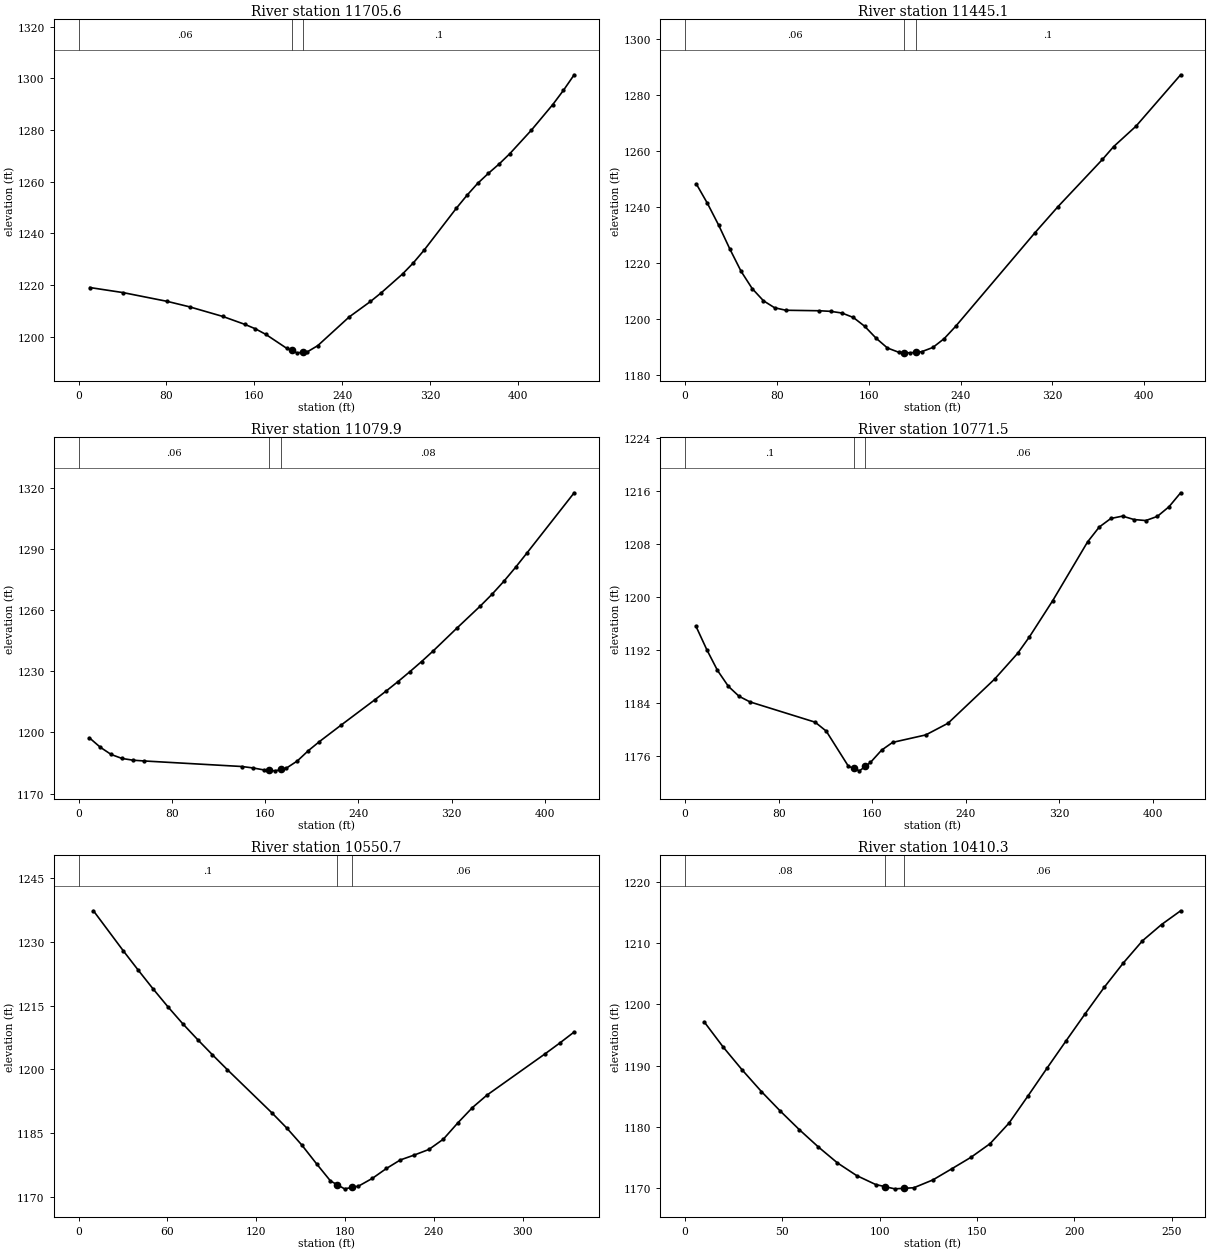
Type RM Length L Ch R = 1 ,11705.6 ,268.8,260.4,252.1
XS GIS Cut Line= 4
     1691405.674      169006.418     1691507.275      168894.123
     1691542.033      168805.891     1691499.254      168605.364
#Sta/Elev= 30
    10.1 1219.05    40.4 1217.09    80.8 1213.68     101 1211.58   131.2 1207.87
   151.4 1204.79   160.9 1203.09   170.4 1200.94   189.4 1195.56   193.9 1194.72
   198.9 1193.78   203.9 1193.99   208.3 1194.17   217.8 1196.57   246.3 1207.63
   265.8 1213.65   275.6 1217.01   295.1 1224.33   304.8 1228.57   314.6 1233.49
   343.9 1249.67   353.7 1254.74   363.4 1259.34   373.2 1263.23     383 1266.85
   392.7 1270.83   412.3 1279.91   431.8 1289.82   441.5 1295.32   451.3 1301.35
#Mann= 3 , 0 , 0
       0     .06       0   193.9    .045       0   203.9      .1       0
Bank Sta=193.9,203.9
XS Rating Curve= 0 ,0
Exp/Cntr=0.3,0.1

Type RM Length L Ch R = 1 ,11445.1 ,362.8,365.2,367.6
XS GIS Cut Line= 4
      1691721.17      169075.934     1691779.992      168963.639
      1691771.97      168765.786     1691769.297      168658.838
#Sta/Elev= 30
     9.8 1248.22    19.5 1241.27    29.3 1233.47      39 1224.99    48.8 1217.02
    58.5 1210.84    68.3  1206.5      78 1204.01    87.8 1203.12     117 1202.94
   126.8 1202.73   136.7 1202.13   146.6 1200.54   156.5 1197.39   166.4 1193.15
   176.3 1189.64   186.2 1188.11   191.1 1188.01   196.1 1187.91   201.1 1188.11
     206  1188.3   215.9 1189.83   225.8    1193   235.7 1197.36     305 1230.87
   324.8 1240.07   363.7    1257   373.4 1261.56   392.9 1268.86   431.8 1287.22
#Mann= 3 , 0 , 0
       0     .06       0   191.1    .045       0   201.1      .1       0
Bank Sta=191.1,201.1
XS Rating Curve= 0 ,0
Exp/Cntr=0.3,0.1

Type RM Length L Ch R = 1 ,11079.9 ,278.2,308.4,338.7
XS GIS Cut Line= 4
     1692095.487      169049.197     1692135.593      168944.923
     1692146.288      168803.217     1692151.635      168632.101
#Sta/Elev= 30
     9.3 1197.27    18.6 1192.68    27.9 1189.14    37.2 1187.19    46.6 1186.34
    55.9 1185.97   140.1 1183.24   149.6 1182.53   159.1 1181.55   163.6 1181.34
   168.6 1181.12   173.6 1181.79     178 1182.39   187.5 1185.93     197 1191.01
   206.5 1195.45   225.4 1203.67   253.8 1215.85   263.9 1220.32     274 1224.92
     284 1229.69   294.1 1234.69   304.2 1239.97   324.3 1251.03   344.5 1261.93
   354.5 1267.66   364.6 1273.99   374.7 1280.87   384.7 1288.08     425 1317.45
#Mann= 3 , 0 , 0
       0     .06       0   163.6    .045       0   173.6     .08       0
Bank Sta=163.6,173.6
XS Rating Curve= 0 ,0
Exp/Cntr=0.3,0.1

Type RM Length L Ch R = 1 ,10771.5 ,232.5,220.8,208.6
XS GIS Cut Line= 4
      1692140.94      169073.261     1692242.541      169067.913
     1692365.531      169070.587     1692496.542       168920.86
#Sta/Elev= 30
     9.2 1195.63    18.5 1192.08    27.7 1188.93      37 1186.53    46.2 1185.02
    55.5 1184.18   111.2 1181.12   120.7 1179.77   139.6 1174.48   144.1 1174.15
   149.1 1173.78   154.1 1174.45   158.5 1175.05     168  1176.9   177.4 1178.07
   205.8  1179.2   224.8 1180.96   264.6 1187.61   284.4 1191.52   294.4 1193.99
   314.3 1199.45   344.1 1208.31   354.1 1210.56     364 1211.85     374 1212.21
   383.9 1211.69   393.9 1211.54   403.8 1212.17   413.8 1213.63   423.7 1215.73
#Mann= 3 , 0 , 0
       0      .1       0   144.1    .045       0   154.1     .06       0
Bank Sta=144.1,154.1
XS Rating Curve= 0 ,0
Exp/Cntr=0.3,0.1

Type RM Length L Ch R = 1 ,10550.7 ,141.4,140.3,139.8
XS GIS Cut Line= 4
     1692282.646      169345.977     1692397.615      169233.682
     1692453.762      169198.924     1692525.952      169118.713
#Sta/Elev= 30
      10 1237.35    30.1 1227.95    40.2 1223.39    50.2 1218.99    60.3 1214.74
    70.3 1210.75    80.4    1207    90.4 1203.42   100.4 1199.94   130.6 1189.73
   140.6 1186.17   150.7 1182.19   160.7 1177.75   170.1 1173.71   174.6 1172.83
   179.6 1171.85   184.6 1172.18     189 1172.48   198.4 1174.32   207.9 1176.65
   217.3 1178.66   226.7 1179.81   236.6 1181.13   246.4 1183.57   256.2 1187.42
     266    1191   275.8 1193.93     315 1203.64   324.8 1206.15   334.7  1208.8
#Mann= 3 , 0 , 0
       0      .1       0   174.6    .045       0   184.6     .06       0
Bank Sta=174.6,184.6
XS Rating Curve= 0 ,0
Exp/Cntr=0.3,0.1

Type RM Length L Ch R = 1 ,10410.3 ,164.9,166.6,167.8
XS GIS Cut Line= 2
     1692392.267      169402.125     1692598.142      169252.398
#Sta/Elev= 28
     9.8 1197.15    19.6 1193.01    29.4 1189.25    39.2 1185.74      49 1182.51
    58.7 1179.49    68.5 1176.65    78.3 1174.04    88.1 1171.98    97.9 1170.51
   102.7 1170.16   107.7  1169.8   112.7 1169.89   117.5 1169.98   127.3 1171.26
   137.1  1173.1   146.9 1174.97   156.7  1177.2   166.4 1180.56   176.2 1185.03
     186 1189.59   195.8 1194.07   205.6  1198.5   215.4 1202.83   225.2 1206.81
     235 1210.43   244.8 1213.09   254.6 1215.34
#Mann= 3 , 0 , 0
       0     .08       0   102.7    .045       0   112.7     .06       0
Bank Sta=102.7,112.7
XS Rating Curve= 0 ,0
Exp/Cntr=0.3,0.1

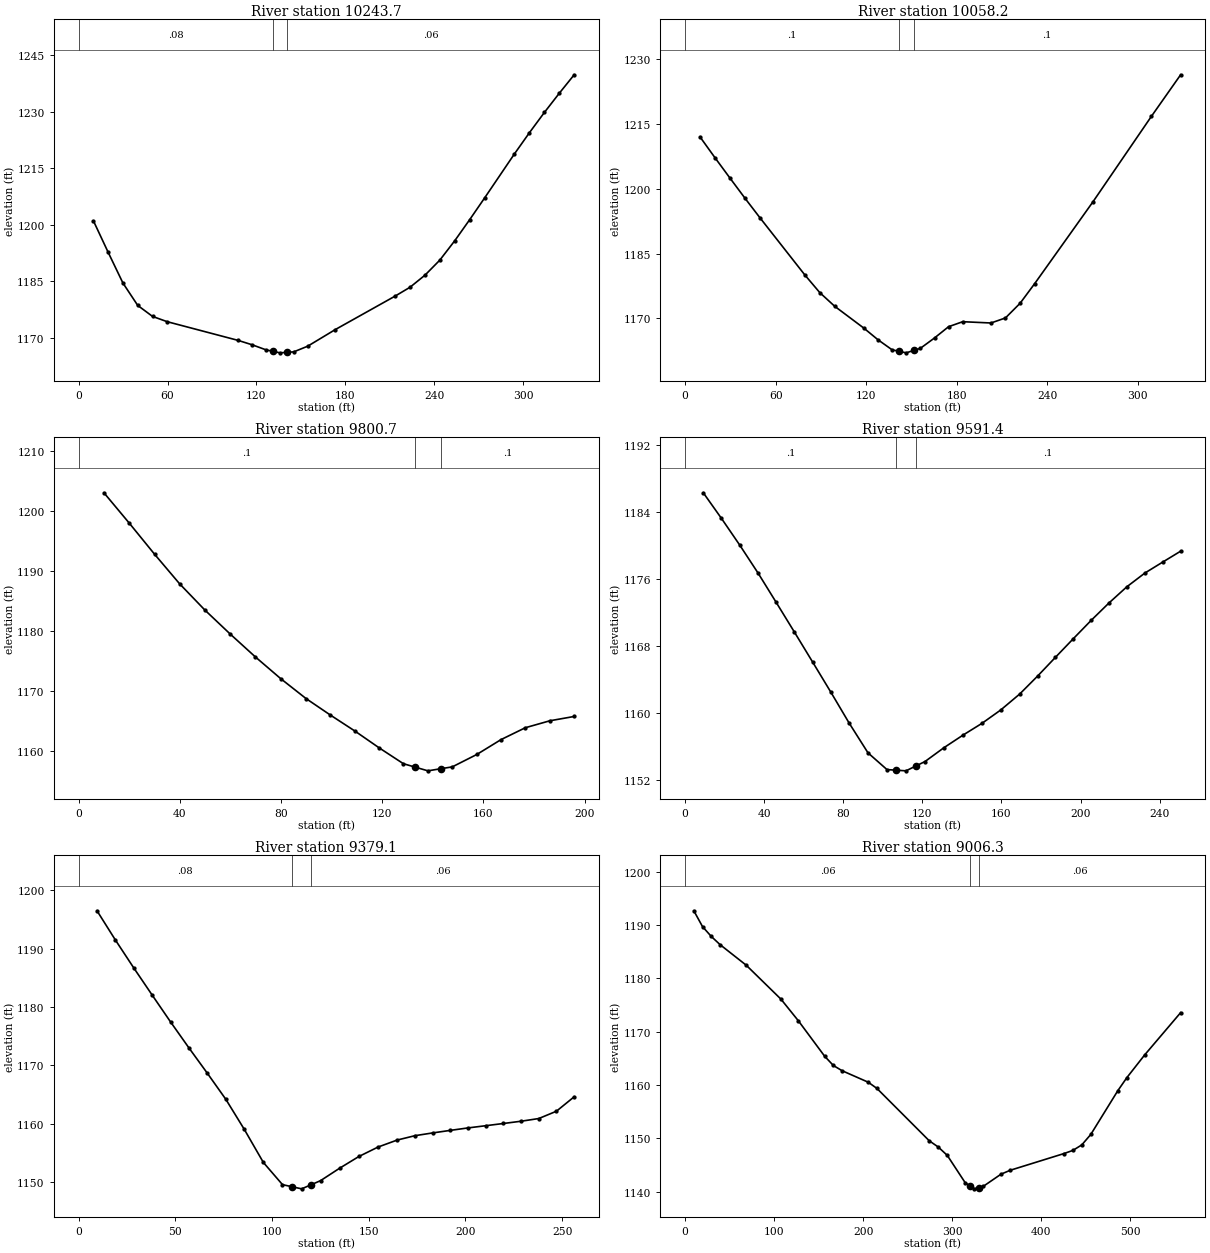
Type RM Length L Ch R = 1 ,10243.7 ,185.4,185.5,185.6
XS GIS Cut Line= 4
     1692464.457      169549.178     1692525.952      169498.378
     1692606.163      169450.251     1692729.153      169345.977
#Sta/Elev= 27
      10    1201    19.9 1192.69    29.9  1184.5    39.9 1178.55    49.9 1175.63
    59.8 1174.23   107.8 1169.25   117.2 1168.09   126.5 1166.75   130.9 1166.38
   135.9 1165.96   140.9  1166.1   145.2 1166.22   154.6 1167.72   173.3 1172.15
   213.6 1181.02   223.7 1183.38   233.8 1186.59   243.8 1190.58   253.9 1195.74
     264 1201.35   274.1 1207.13   294.2 1218.81   304.3 1224.43   314.4 1229.81
   324.5 1234.93   334.5 1239.81
#Mann= 3 , 0 , 0
       0     .08       0   130.9    .045       0   140.9     .06       0
Bank Sta=130.9,140.9
XS Rating Curve= 0 ,0
Exp/Cntr=0.3,0.1

Type RM Length L Ch R = 1 ,10058.2 ,258.5,257.5,256.6
XS GIS Cut Line= 4
     1692550.015      169696.231     1692643.595      169640.084
     1692723.806      169591.957     1692822.732       169514.42
#Sta/Elev= 25
     9.9 1212.04    19.8 1207.22    29.8 1202.47    39.7 1197.82    49.6  1193.3
    79.4 1180.02    89.3 1175.93    99.2 1172.76   118.5  1167.7   127.8 1165.02
   137.2 1162.68   141.5 1162.36   146.5 1161.98   151.5 1162.53   155.9 1163.02
   165.3 1165.43   174.6 1168.04     184  1169.2   202.7  1168.9   212.3 1170.07
     222 1173.47   231.7 1178.04   270.4 1197.05     309  1216.8   328.4 1226.45
#Mann= 3 , 0 , 0
       0      .1       0   141.5    .045       0   151.5      .1       0
Bank Sta=141.5,151.5
XS Rating Curve= 0 ,0
Exp/Cntr=0.3,0.1

Type RM Length L Ch R = 1 ,9800.7  ,202.9,209.3,215.7
XS GIS Cut Line= 3
     1692681.026      169918.148     1692758.564      169872.695
     1692846.795      169813.874
#Sta/Elev= 22
      10 1203.09      20 1198.03      30 1192.84    39.9  1187.9    49.9 1183.51
    59.9 1179.51    69.9 1175.67    79.9 1172.05    89.9 1168.73    99.5 1165.98
   109.2 1163.31   118.8  1160.5   128.4 1157.85   133.1 1157.27   138.1 1156.66
   143.1 1157.01   147.7 1157.32   157.4 1159.39     167 1161.88   176.6 1163.86
   186.3 1165.02   195.9 1165.74
#Mann= 3 , 0 , 0
       0      .1       0   133.1    .045       0   143.1      .1       0
Bank Sta=133.1,143.1
XS Rating Curve= 0 ,0
Exp/Cntr=0.3,0.1

Type RM Length L Ch R = 1 ,9591.4  ,211,212.3,213.6
XS GIS Cut Line= 4
     1692795.995      170062.527     1692873.532      170033.117
     1692956.417      170009.053     1693012.564      169950.232
#Sta/Elev= 29
     9.2 1186.33    18.4 1183.26    27.6 1180.08    36.9 1176.72    46.1  1173.2
    55.3 1169.65    64.5 1166.07    73.7 1162.47    82.9 1158.79    92.5  1155.2
   102.1  1153.2   106.7 1153.13   111.7 1153.05   116.7 1153.63   121.3 1154.16
   130.9 1155.82   140.5 1157.32   150.1 1158.73   159.6 1160.33   169.2 1162.24
   178.3  1164.4   187.3 1166.64   196.3 1168.86   205.4 1171.07   214.4 1173.15
   223.4 1175.08   232.5 1176.72   241.5 1178.03   250.6 1179.34
#Mann= 3 , 0 , 0
       0      .1       0   106.7    .045       0   116.7      .1       0
Bank Sta=106.7,116.7
XS Rating Curve= 0 ,0
Exp/Cntr=0.3,0.1

Type RM Length L Ch R = 1 ,9379.1  ,397.7,372.8,347.9
XS GIS Cut Line= 4
     1692812.037      170233.644     1692897.596      170233.644
     1692975.133      170217.601     1693047.322      170161.454
#Sta/Elev= 29
     9.5  1196.5      19 1191.49    28.5  1186.7      38 1182.05    47.5 1177.45
      57 1172.99    66.5 1168.65    76.1 1164.16    85.6 1159.03    95.5 1153.33
   105.4 1149.52   110.2 1149.17   115.3  1148.8   120.2  1149.5   125.1 1150.21
     135 1152.35   144.9 1154.35   154.8 1155.97   164.7 1157.17   173.9 1157.92
     183 1158.39   192.2 1158.83   201.3 1159.25   210.5 1159.63   219.6 1160.01
   228.8  1160.4   237.9 1160.86     247 1162.11   256.2 1164.59
#Mann= 3 , 0 , 0
       0     .08       0   110.2    .045       0   120.2     .06       0
Bank Sta=110.2,120.2
XS Rating Curve= 0 ,0
Exp/Cntr=0.3,0.1

Type RM Length L Ch R = 1 ,9006.3  ,216.2,229.4,242.7
XS GIS Cut Line= 4
      1692871.86      170681.413     1693100.796      170530.424
     1693116.839      170420.802     1693127.533      170249.686
#Sta/Elev= 30
     9.8 1192.69    19.6 1189.71    29.4 1187.88    39.2 1186.35    68.6 1182.49
   107.7 1176.11   127.3 1172.04   156.7 1165.42   166.5 1163.68   176.3  1162.7
   205.7 1160.54   215.5 1159.37   274.2 1149.56   284.3 1148.39   294.4 1146.83
   314.5 1141.71   319.6 1141.12   324.6 1140.55   329.6 1140.77   334.7    1141
   354.8  1143.3   364.9 1144.02   425.4 1147.16   435.5 1147.76   445.5 1148.79
   455.6 1150.75   485.9 1158.94     496 1161.38   516.1 1165.66   556.5 1173.59
#Mann= 3 , 0 , 0
       0     .06       0   319.6    .045       0   329.6     .06       0
Bank Sta=319.6,329.6
XS Rating Curve= 0 ,0
Exp/Cntr=0.3,0.1

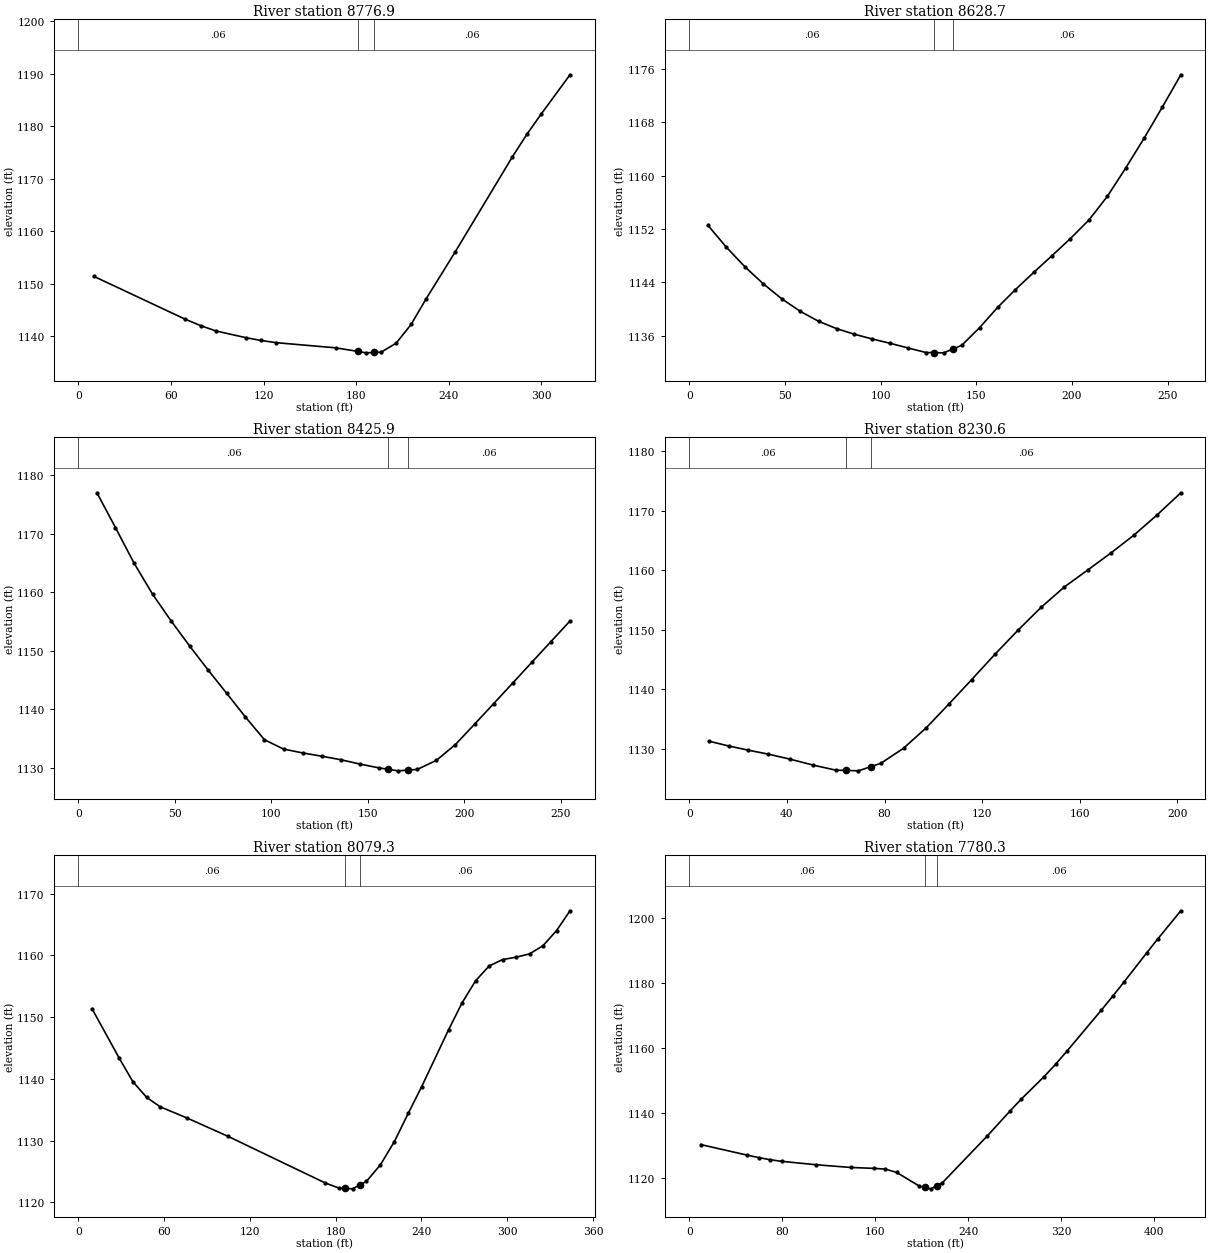
Type RM Length L Ch R = 1 ,8776.9  ,144.7,148.2,151.6
XS GIS Cut Line= 4
     1693146.466       170612.73     1693235.412      170617.057
     1693333.569       170522.47     1693359.277       170432.87
#Sta/Elev= 20
     9.9 1151.44    69.3 1143.25    79.2 1142.04    89.1 1141.03   108.5 1139.75
   118.3 1139.22     128  1138.8   166.9 1137.81   181.4 1137.12   186.4 1136.86
   191.4 1136.93   196.2 1136.99   205.9 1138.69   215.6 1142.26   225.4 1147.17
     244 1155.99   281.3 1174.21   290.6 1178.45   299.9 1182.33   318.6 1189.82
#Mann= 3 , 0 , 0
       0     .06       0   181.4    .045       0   191.4     .06       0
Bank Sta=181.4,191.4
XS Rating Curve= 0 ,0
Exp/Cntr=0.3,0.1

Type RM Length L Ch R = 1 ,8628.7  ,205.3,202.8,200.4
XS GIS Cut Line= 4
     1693278.272      170736.298      1693337.31      170703.347
     1693422.434      170645.682     1693485.591      170586.644
#Sta/Elev= 29
     9.7 1152.56    19.3 1149.29      29 1146.35    38.6 1143.79    48.3 1141.53
      58 1139.64    67.6 1138.15      77 1137.05    86.3 1136.21    95.7 1135.49
     105 1134.85   114.3 1134.15   123.7 1133.47     128 1133.45     133 1133.42
     138 1134.02   142.4 1134.55   151.7 1137.19   161.1 1140.22   170.4 1142.89
     180 1145.48   189.6    1148   199.2 1150.56   208.9 1153.35   218.5 1156.89
   228.1 1161.14   237.7  1165.6   247.3 1170.31   256.9 1175.12
#Mann= 3 , 0 , 0
       0     .06       0     128    .045       0     138     .06       0
Bank Sta=128,138
XS Rating Curve= 0 ,0
Exp/Cntr=0.3,0.1

Type RM Length L Ch R = 1 ,8425.9  ,199.7,195.3,190.9
XS GIS Cut Line= 3
     1693364.228      170899.694     1693449.303      170883.866
     1693575.927       170773.07
#Sta/Elev= 28
     9.6 1177.01    19.2 1171.06    28.8 1165.01    38.5 1159.65    48.1 1155.09
    57.7 1150.81    67.3  1146.7    76.9 1142.73    86.5 1138.73    96.4 1134.83
   106.3 1133.23   116.2 1132.57   126.1 1132.01     136 1131.41   145.9 1130.67
   155.8 1130.01   160.7 1129.76   165.7 1129.51   170.7 1129.63   175.6 1129.75
   185.5 1131.29   195.4    1134   205.3 1137.47   215.2 1140.98   225.1  1144.5
     235 1148.05   244.9 1151.58   254.8 1155.11
#Mann= 3 , 0 , 0
       0     .06       0   160.7    .045       0   170.7     .06       0
Bank Sta=160.7,170.7
XS Rating Curve= 0 ,0
Exp/Cntr=0.3,0.1

Type RM Length L Ch R = 1 ,8230.6  ,149.5,151.3,153.1
XS GIS Cut Line= 4
     1693614.651      171005.402     1693639.365      170984.807
     1693688.792      170917.531       1693734.1      170844.763
#Sta/Elev= 24
       8 1131.26    16.1 1130.45    24.1 1129.75    32.2 1129.09    41.4 1128.22
    50.7 1127.24      60 1126.39    64.3 1126.34    69.3 1126.27    74.3 1126.96
    78.5 1127.54    87.8 1130.07    97.1 1133.51   106.4 1137.51   115.7  1141.6
   125.2 1145.84   134.7 1149.91   144.2 1153.77   153.7 1157.18   163.3 1160.03
   172.8  1162.9   182.3 1165.92   191.8 1169.33   201.4    1173
#Mann= 3 , 0 , 0
       0     .06       0    64.3    .045       0    74.3     .06       0
Bank Sta=64.3,74.3
XS Rating Curve= 0 ,0
Exp/Cntr=0.3,0.1

Type RM Length L Ch R = 1 ,8079.3  ,306.1,298.9,290.3
XS GIS Cut Line= 4
     1693631.127      171186.635     1693732.728      171100.137
     1693797.258      171027.369     1693824.717      170917.531
#Sta/Elev= 27
     9.5 1151.38    28.6 1143.34    38.1 1139.55    47.7 1137.02    57.2 1135.49
    76.2 1133.65   104.8 1130.69   172.3 1123.19   182.1 1122.33   186.8 1122.27
   191.8  1122.2   196.8 1122.83   201.5 1123.42   211.2 1126.07     221 1129.84
   230.7 1134.41   240.1 1138.74     259 1147.99   268.4 1152.33   277.9 1155.92
   287.3 1158.29   296.7 1159.34   306.2 1159.72   315.6 1160.26     325 1161.58
   334.5 1164.03   343.9 1167.24
#Mann= 3 , 0 , 0
       0     .06       0   186.8    .045       0   196.8     .06       0
Bank Sta=186.8,196.8
XS Rating Curve= 0 ,0
Exp/Cntr=0.3,0.1

Type RM Length L Ch R = 1 ,7780.3  ,172.1,172.2,172.4
XS GIS Cut Line= 4
     1693879.636      171361.003     1693986.728       171230.57
     1694021.053      171160.548      1694005.95      170984.807
#Sta/Elev= 27
     9.9 1130.36    49.6 1127.13    59.6 1126.38    69.5 1125.71    79.4 1125.22
   109.2 1124.16     139 1123.33   158.8 1123.05   168.8 1122.82   178.5  1121.8
     198 1117.61   202.8 1117.19   207.8 1116.76   212.8 1117.65   217.5 1118.49
   256.5 1133.01   276.1 1140.68   285.9 1144.38   305.5 1151.27   315.3 1155.03
   325.1 1159.08   354.5 1171.58   364.3 1175.87   374.1 1180.26   393.7 1189.25
   403.5 1193.66   423.1 1202.19
#Mann= 3 , 0 , 0
       0     .06       0   202.8    .045       0   212.8     .06       0
Bank Sta=202.8,212.8
XS Rating Curve= 0 ,0
Exp/Cntr=0.3,0.1

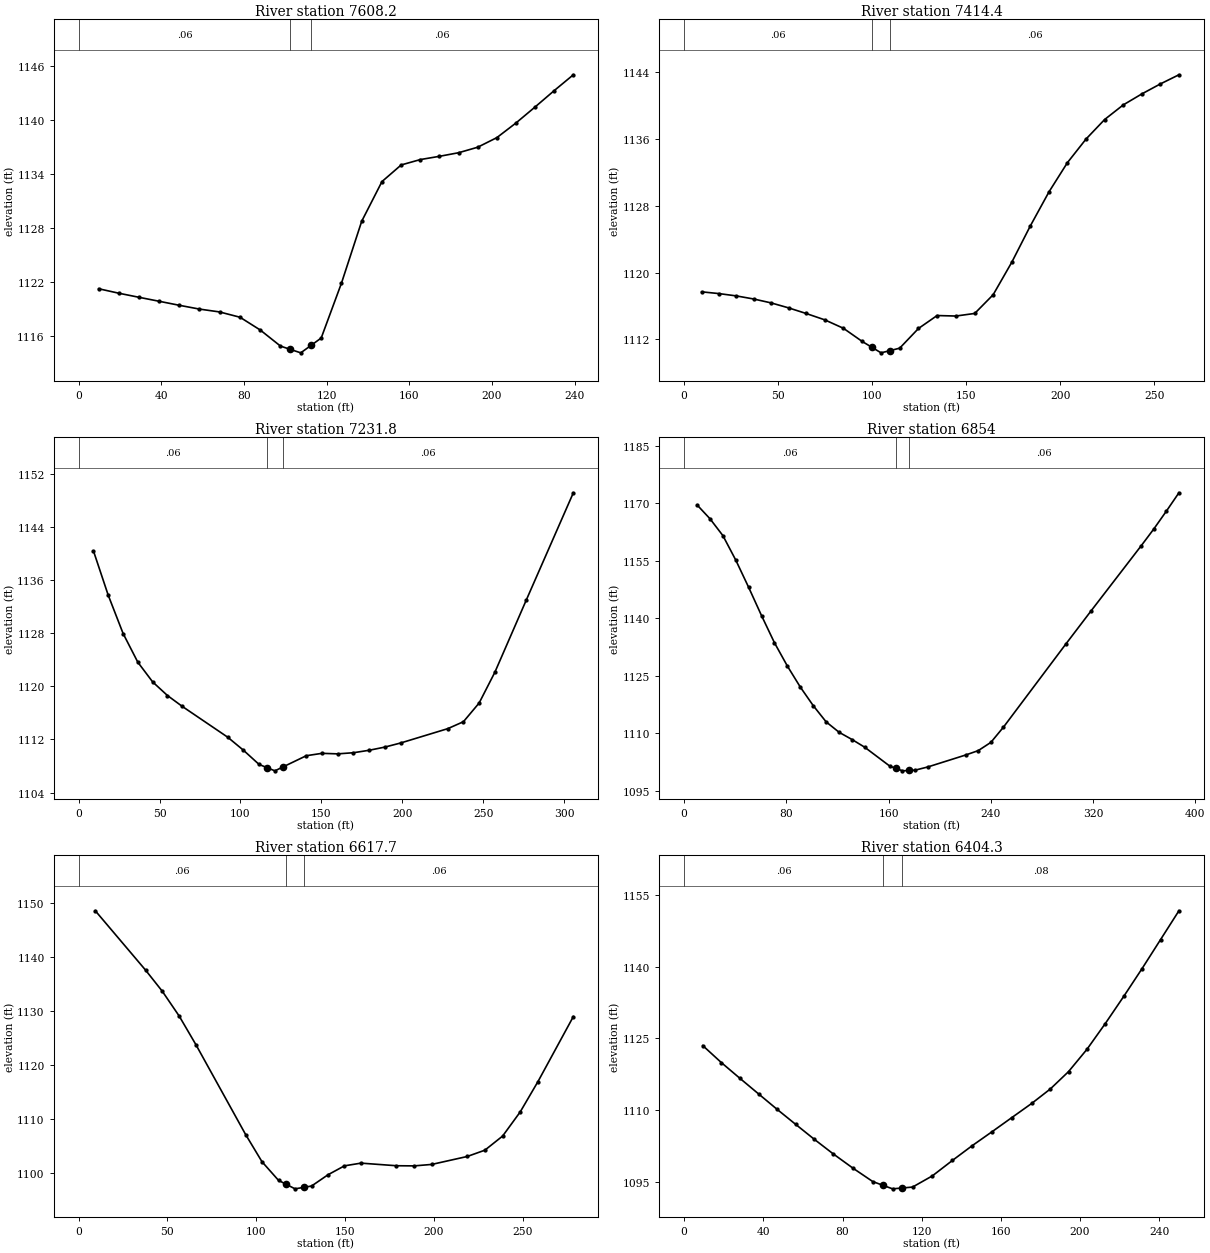
Type RM Length L Ch R = 1 ,7608.2  ,194.1,193.8,193.2
XS GIS Cut Line= 4
      1694097.94      171380.225     1694126.772      171329.425
     1694167.962      171251.165     1694221.508      171175.651
#Sta/Elev= 27
     9.7 1121.21    19.5 1120.71    29.2 1120.26    38.9 1119.82    48.7 1119.37
    58.4 1118.95    68.2 1118.63    78.1 1118.04    87.9 1116.62    97.7 1114.83
   102.5 1114.46   107.5 1114.08   112.5 1114.91   117.4 1115.73   127.2 1121.83
     137 1128.72   146.8 1133.13   156.1 1134.98   165.4 1135.58   174.6 1135.94
   183.9 1136.34   193.1 1136.95   202.4 1138.02   211.6 1139.64   220.9 1141.43
   230.2 1143.26   239.4 1145.01
#Mann= 3 , 0 , 0
       0     .06       0   102.5    .045       0   112.5     .06       0
Bank Sta=102.5,112.5
XS Rating Curve= 0 ,0
Exp/Cntr=0.3,0.1

Type RM Length L Ch R = 1 ,7414.4  ,179,182.6,186.2
XS GIS Cut Line= 4
      1694250.34      171483.198     1694288.783      171431.025
     1694327.227      171350.019     1694357.432      171245.673
#Sta/Elev= 29
     9.3  1117.7    18.5 1117.49    27.8 1117.21      37 1116.84    46.3 1116.37
    55.5 1115.78    64.8 1115.11    74.8 1114.34    84.7 1113.33    94.7 1111.75
    99.7 1111.07   104.7 1110.39   109.7 1110.67   114.6 1110.95   124.6 1113.31
   134.5 1114.86   144.5  1114.8   154.5 1115.11   164.3 1117.35   174.2 1121.24
   184.1 1125.61     194 1129.68   203.8 1133.18   213.7 1136.01   223.6 1138.35
   233.5  1140.1   243.4 1141.42   253.2 1142.61   263.1 1143.71
#Mann= 3 , 0 , 0
       0     .06       0    99.7    .045       0   109.7     .06       0
Bank Sta=99.7,109.7
XS Rating Curve= 0 ,0
Exp/Cntr=0.3,0.1

Type RM Length L Ch R = 1 ,7231.8  ,380.6,377.8,375.1
XS GIS Cut Line= 4
     1694405.487      171598.528     1694438.438      171523.014
     1694483.746      171459.858     1694553.768      171332.171
#Sta/Elev= 26
     9.2 1140.42    18.3 1133.76    27.5 1127.98    36.6 1123.65    45.8 1120.67
    54.9 1118.63    64.1 1116.98    92.1 1112.35   101.8 1110.39   111.5 1108.24
   116.3 1107.76   121.3 1107.27   126.3 1107.86   140.7 1109.55   150.4 1109.91
   160.1 1109.83   169.8    1110   179.5 1110.37   189.2 1110.85     199 1111.47
   228.1 1113.63   237.8 1114.68   247.5  1117.5   257.2 1122.13   276.6 1133.01
   305.7  1149.2
#Mann= 3 , 0 , 0
       0     .06       0   116.3    .045       0   126.3     .06       0
Bank Sta=116.3,126.3
XS Rating Curve= 0 ,0
Exp/Cntr=0.3,0.1

Type RM Length L Ch R = 1 ,6854    ,236.4,236.3,236.1
XS GIS Cut Line= 4
     1694681.455      171815.459     1694767.953      171716.604
     1694818.753      171620.496      1694868.18      171481.825
#Sta/Elev= 30
    10.1 1169.54    20.2 1165.94    30.3 1161.55    40.4 1155.16    50.5 1148.05
    60.6 1140.67    70.7 1133.61    80.8 1127.55    90.9 1122.09     101 1117.26
   111.1 1113.03   121.3  1110.3   131.4 1108.42   141.2 1106.44     161 1101.48
   165.9 1100.88   170.9 1100.26   175.9 1100.35   180.8 1100.44   190.7 1101.27
   220.3 1104.38   230.2 1105.53   240.1 1107.68   249.9 1111.63   298.9 1133.36
   318.6 1141.97   357.8 1158.92   367.7 1163.31   377.5 1167.94   387.3 1172.71
#Mann= 3 , 0 , 0
       0     .06       0   165.9    .045       0   175.9     .06       0
Bank Sta=165.9,175.9
XS Rating Curve= 0 ,0
Exp/Cntr=0.3,0.1

Type RM Length L Ch R = 1 ,6617.7  ,219.4,213.4,207.4
XS GIS Cut Line= 4
     1694921.726      171915.686     1694962.916      171852.529
     1695001.359      171778.388     1695004.105      171658.939
#Sta/Elev= 24
     9.4  1148.5    37.7 1137.53    47.1 1133.63    56.6 1129.05      66 1123.77
      94 1107.15   103.2 1102.13   112.5 1098.69   116.8 1097.96   121.8 1097.12
   126.8  1097.4   131.1 1097.64   140.4 1099.73   149.6 1101.37   158.9 1101.87
   178.8 1101.39   188.8 1101.36   198.7 1101.63   218.7  1103.1   228.6 1104.26
   238.6 1106.87   248.5 1111.33   258.5 1116.94   278.4 1128.95
#Mann= 3 , 0 , 0
       0     .06       0   116.8    .045       0   126.8     .06       0
Bank Sta=116.8,126.8
XS Rating Curve= 0 ,0
Exp/Cntr=0.3,0.1

Type RM Length L Ch R = 1 ,6404.3  ,396.5,415.8,435.4
XS GIS Cut Line= 4
     1695155.133       171977.47     1695182.592      171907.448
     1695200.441      171808.594     1695215.544      171735.826
#Sta/Elev= 28
     9.4 1123.46    18.8  1119.9    28.2  1116.6    37.6 1113.35      47 1110.11
    56.4 1106.96    65.8 1103.84    75.2 1100.84    85.3 1097.81    95.3 1095.01
   100.3 1094.25   105.3 1093.49   110.3 1093.67   115.4 1093.86   125.4  1096.2
   135.5 1099.42   145.5 1102.51   155.6 1105.45   165.6 1108.41   175.7 1111.39
     185 1114.38   194.2 1118.01   203.5 1122.67   212.8 1128.08   222.1 1133.75
   231.4 1139.59   240.7 1145.63     250 1151.67
#Mann= 3 , 0 , 0
       0     .06       0   100.3    .045       0   110.3     .08       0
Bank Sta=100.3,110.3
XS Rating Curve= 0 ,0
Exp/Cntr=0.3,0.1

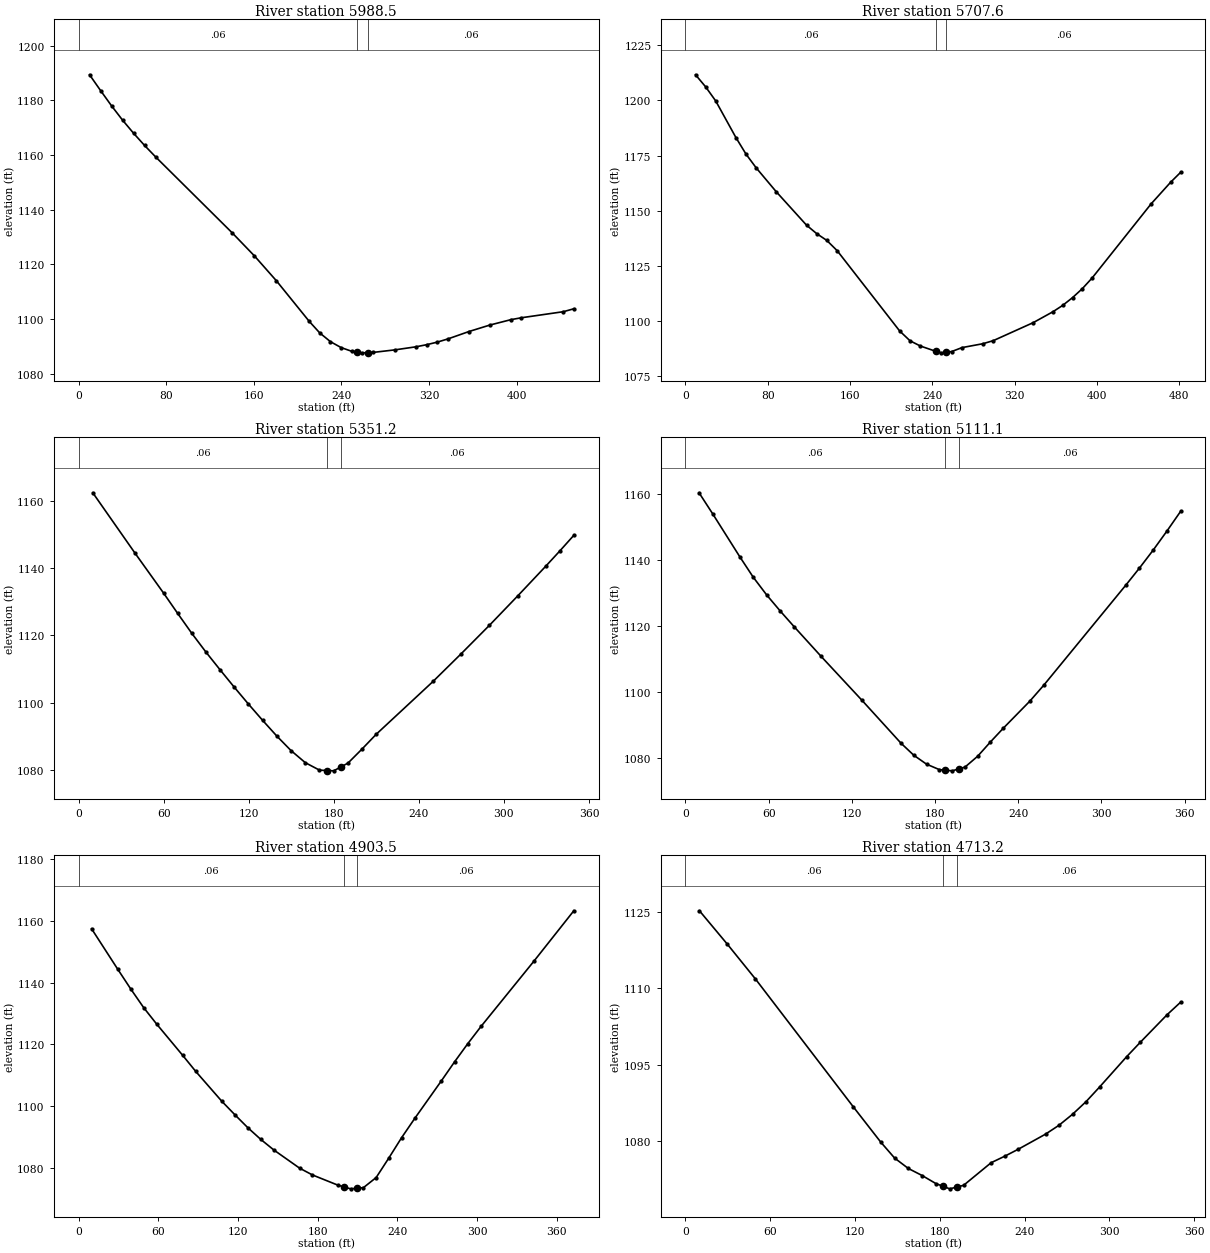
Type RM Length L Ch R = 1 ,5988.5  ,275.8,280.8,285.7
XS GIS Cut Line= 4
     1695267.033      172193.011     1695449.125      172108.535
     1695582.409      172048.463     1695636.849      171958.356
#Sta/Elev= 30
      10 1189.37    20.1 1183.57    30.1 1177.99    40.1 1172.78    50.2 1167.96
    60.2 1163.51    70.3 1159.31   140.5  1131.4   160.6 1123.04   180.7 1113.91
   210.5 1099.14   220.2 1094.86     230 1091.65   239.7  1089.5   249.5 1088.12
   254.2 1087.85   259.2 1087.57   264.2 1087.65     269 1087.73   288.5 1088.64
   307.9 1089.77   317.7 1090.54   327.4 1091.48   337.2 1092.66   356.5 1095.38
   375.6 1097.75   394.8 1099.72   404.4 1100.42   442.6 1102.63   452.2  1103.7
#Mann= 3 , 0 , 0
       0     .06       0   254.2    .045       0   264.2     .06       0
Bank Sta=254.2,264.2
XS Rating Curve= 0 ,0
Exp/Cntr=0.3,0.1

Type RM Length L Ch R = 1 ,5707.6  ,358.8,356.5,354.1
XS GIS Cut Line= 4
     1695355.263      172373.226     1695492.301      172363.839
     1695661.253      172331.926     1695800.168      172230.556
#Sta/Elev= 30
     9.8 1211.65    19.6 1206.18    29.4 1199.78    49.1  1183.1    58.9  1175.6
    68.7 1169.42    88.3 1158.52   117.7 1143.36   127.5 1139.55   137.4 1136.44
   147.5 1131.77   208.2 1095.33   218.3 1090.87   228.4 1088.49   243.6 1086.06
   248.6 1085.41   253.6  1085.7   258.7 1085.99   268.8 1087.79   289.1 1089.55
   299.2 1090.95     338 1099.12   357.1 1104.05   366.6 1106.94   376.2 1110.47
   385.7 1114.53   395.3 1119.42   452.6 1153.05   471.7 1162.93   481.3 1167.37
#Mann= 3 , 0 , 0
       0     .06       0   243.6    .045       0   253.6     .06       0
Bank Sta=243.6,253.6
XS Rating Curve= 0 ,0
Exp/Cntr=0.3,0.1

Type RM Length L Ch R = 1 ,5351.2  ,251.9,240.1,228.3
XS GIS Cut Line= 4
     1695522.337      172731.778     1695648.112      172699.865
     1695743.851      172669.829     1695843.345      172604.126
#Sta/Elev= 27
      10  1162.4    39.9 1144.37    59.9 1132.58    69.9  1126.5    79.9 1120.55
    89.8 1115.02    99.8 1109.73   109.8 1104.56   119.8 1099.54   129.8  1094.7
   139.8 1090.03   149.8 1085.72   159.9 1082.11   169.9 1079.89   174.9 1079.78
   179.9 1079.68   184.9 1080.82     190 1081.98     200  1086.2     210 1090.59
     250 1106.27   269.8 1114.49   289.7 1122.94   309.6 1131.66   329.5 1140.55
   339.4 1145.08   349.3 1149.74
#Mann= 3 , 0 , 0
       0     .06       0   174.9    .045       0   184.9     .06       0
Bank Sta=174.9,184.9
XS Rating Curve= 0 ,0
Exp/Cntr=0.3,0.1

Type RM Length L Ch R = 1 ,5111.1  ,204.5,207.6,210.6
XS GIS Cut Line= 4
     1695681.902      173002.101      1695792.66      172921.379
     1695856.486      172842.535     1695931.575      172750.551
#Sta/Elev= 27
     9.8 1160.29    19.6 1153.95    39.2 1140.91    48.9 1134.72    58.7 1129.29
    68.5 1124.42    78.3 1119.78    97.9 1110.73   127.3 1097.46   155.5 1084.45
   164.7 1080.81   173.9 1078.11   183.2 1076.45   187.4 1076.29   192.4 1076.09
   197.4  1076.7   201.6 1077.21   210.8 1080.52     220 1084.84   229.3 1089.01
   248.4 1097.19   258.3 1101.94   317.7 1132.35   327.5  1137.5   337.4 1142.94
   347.3  1148.7   357.2 1154.68
#Mann= 3 , 0 , 0
       0     .06       0   187.4    .045       0   197.4     .06       0
Bank Sta=187.4,197.4
XS Rating Curve= 0 ,0
Exp/Cntr=0.3,0.1

Type RM Length L Ch R = 1 ,4903.5  ,177.7,190.3,203
XS GIS Cut Line= 4
      1695792.66      173150.402     1695925.943      173067.804
      1695989.77      173009.609     1696070.491      172908.239
#Sta/Elev= 29
     9.8 1157.41    29.4 1144.38    39.2 1137.99      49 1131.91    58.8 1126.58
    78.4 1116.46    88.2 1111.28   107.8 1101.64   117.6 1097.29   127.4 1093.08
   137.2 1089.28     147 1085.87   166.4 1079.99     176 1077.81   195.2  1074.5
   199.8 1073.93   204.8 1073.31   209.8 1073.51   214.4 1073.69     224 1076.96
   233.6 1083.32   243.2 1089.89   253.1 1096.12   273.1 1108.24     283 1114.37
     293 1120.28     303 1125.87   342.9 1147.02   372.8 1163.25
#Mann= 3 , 0 , 0
       0     .06       0   199.8    .045       0   209.8     .06       0
Bank Sta=199.8,209.8
XS Rating Curve= 0 ,0
Exp/Cntr=0.3,0.1

Type RM Length L Ch R = 1 ,4713.2  ,120.2,133.6,147
XS GIS Cut Line= 4
     1695879.012      173195.456     1695987.892      173199.211
     1696104.281       173186.07     1696213.161      173125.998
#Sta/Elev= 25
     9.9 1125.19    29.7 1118.61    49.5 1111.81   118.7 1086.72   138.2 1079.77
     148 1076.64   157.7  1074.6   167.5 1073.21   177.3 1071.62     182 1071.13
     187  1070.6     192 1070.95   196.8 1071.29   216.3 1075.73   226.1 1077.03
   235.6 1078.39   254.8 1081.34   264.3 1083.08   273.9 1085.24   283.5 1087.73
     293 1090.58   312.2 1096.55   321.7 1099.33   340.9 1104.81   350.4 1107.25
#Mann= 3 , 0 , 0
       0     .06       0     182    .045       0     192     .06       0
Bank Sta=182,192
XS Rating Curve= 0 ,0
Exp/Cntr=0.3,0.1

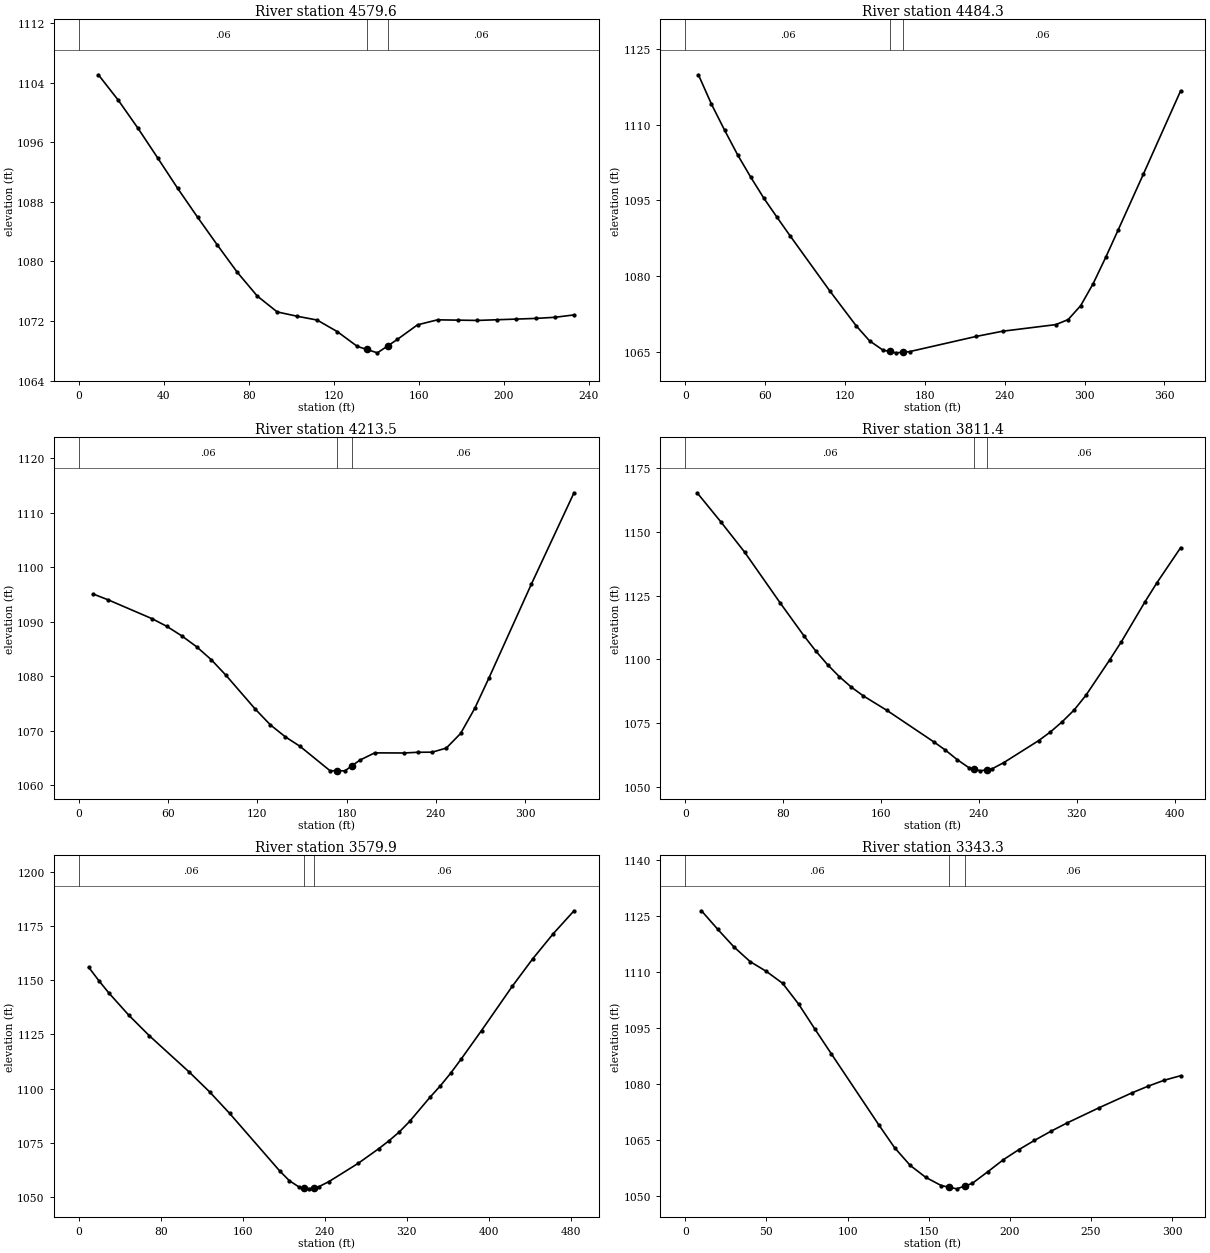
Type RM Length L Ch R = 1 ,4579.6  ,99.5,95.3,91.1
XS GIS Cut Line= 4
     1695937.207      173278.055     1696019.805      173293.072
     1696108.036      173347.512     1696147.458      173370.039
#Sta/Elev= 27
     9.3 1105.05    18.7 1101.62      28 1097.84    37.3 1093.84    46.6  1089.8
      56 1085.91    65.3 1082.18    74.6 1078.55      84 1075.36    93.4 1073.22
   102.8 1072.64   112.2 1072.13   121.7 1070.57   131.1 1068.59   135.5 1068.19
   140.5 1067.73   145.5 1068.68   149.9 1069.53   159.4 1071.49   168.8 1072.16
   178.2 1072.12   187.6 1072.08   196.7 1072.17   205.8 1072.26   214.9 1072.35
     224  1072.5     233 1072.82
#Mann= 3 , 0 , 0
       0     .06       0   135.5    .045       0   145.5     .06       0
Bank Sta=135.5,145.5
XS Rating Curve= 0 ,0
Exp/Cntr=0.3,0.1

Type RM Length L Ch R = 1 ,4484.3  ,277.6,270.8,263.9
XS GIS Cut Line= 4
     1695863.995      173321.231     1695957.856      173375.671
     1696117.422      173433.865     1696211.284      173435.743
#Sta/Elev= 26
     9.9 1119.85    19.7 1114.03    29.6 1108.86    39.5 1103.92    49.3 1099.53
    59.2 1095.35      69 1091.61    78.9 1087.91   108.5 1077.08   128.5 1070.11
   138.5 1067.15   148.5 1065.33   153.5 1065.06   158.5 1064.78   163.5  1064.9
   168.5 1065.02   218.4 1068.02   238.4 1069.06   278.4 1070.37   287.7 1071.37
   297.1 1074.13   306.5  1078.5   315.9 1083.69   325.3 1089.14   344.1 1100.12
   372.2 1116.68
#Mann= 3 , 0 , 0
       0     .06       0   153.5    .045       0   163.5     .06       0
Bank Sta=153.5,163.5
XS Rating Curve= 0 ,0
Exp/Cntr=0.3,0.1

Type RM Length L Ch R = 1 ,4213.5  ,401.1,402.1,403.2
XS GIS Cut Line= 4
     1695777.642      173632.853     1695895.908      173644.116
     1695986.015      173644.116     1696109.913      173645.993
#Sta/Elev= 27
     9.9 1095.06    19.8 1094.01    49.5 1090.52    59.4 1089.11    69.3 1087.38
    79.2  1085.4    89.1 1083.01      99 1080.14   118.8 1073.89   128.8 1071.04
   138.8 1068.85   148.8 1067.08   168.9 1062.61   173.9  1062.6   178.9 1062.59
   183.9 1063.57   188.9 1064.55   198.9 1065.89   218.4 1065.87     228    1066
   237.5 1066.02     247 1066.77   256.6 1069.45   266.1 1074.06   275.6 1079.62
   304.2 1096.92   332.8 1113.67
#Mann= 3 , 0 , 0
       0     .06       0   173.9    .045       0   183.9     .06       0
Bank Sta=173.9,183.9
XS Rating Curve= 0 ,0
Exp/Cntr=0.3,0.1

Type RM Length L Ch R = 1 ,3811.4  ,232.6,231.5,230.4
XS GIS Cut Line= 4
     1695741.974      174040.213     1695916.557      174038.336
     1696049.841      174045.845      1696145.58      174030.827
#Sta/Elev= 30
     9.7 1165.22    29.1 1153.84    48.5 1142.02    77.6 1122.11      97 1109.25
   106.7 1103.29   116.4  1097.9   126.1 1093.18   135.8 1089.13   145.5 1085.74
   164.9 1080.03   203.2 1067.71   212.7 1064.48   222.3 1060.76   231.8 1057.64
   236.3 1057.04   241.3 1056.37   246.3 1056.79   250.9 1057.18   260.4 1059.59
     289 1068.23   298.6 1071.62   308.1 1075.55   317.8 1080.12   327.5  1085.9
   346.9 1099.74   356.5 1106.88   375.9 1122.58   385.6 1129.99     405 1143.74
#Mann= 3 , 0 , 0
       0     .06       0   236.3    .045       0   246.3     .06       0
Bank Sta=236.3,246.3
XS Rating Curve= 0 ,0
Exp/Cntr=0.3,0.1

Type RM Length L Ch R = 1 ,3579.9  ,236.3,236.6,237
XS GIS Cut Line= 4
     1695775.764      174261.727     1695952.225      174272.991
     1696047.964      174272.991     1696256.337      174242.955
#Sta/Elev= 30
     9.8 1155.98    19.6 1149.86    29.5  1144.1    49.1 1133.76    68.8 1124.44
   108.1  1107.5   127.7 1098.47   147.3 1088.51     196 1062.02   205.5 1057.47
   215.1 1054.51   219.7 1054.13   224.7 1053.71   229.7 1054.24   234.3 1054.73
   243.8 1056.97   272.6 1065.47   292.6 1072.22   302.6 1075.87   312.7 1079.96
   322.7 1084.79   342.7    1096   352.8 1101.28   362.8 1107.09   372.8 1113.44
   392.9 1126.77   422.9  1147.2     443 1159.98     463 1171.55   483.1 1182.04
#Mann= 3 , 0 , 0
       0     .06       0   219.7    .045       0   229.7     .06       0
Bank Sta=219.7,229.7
XS Rating Curve= 0 ,0
Exp/Cntr=0.3,0.1

Type RM Length L Ch R = 1 ,3343.3  ,90.6,94.8,99
XS GIS Cut Line= 4
     1695841.468      174492.628     1695950.348      174507.646
     1696055.473      174509.523      1696145.58        174511.4
#Sta/Elev= 29
      10 1126.48      20 1121.52      30 1116.78      40 1112.84      50 1110.22
      60 1107.02    69.9 1101.42    79.9 1094.74    89.9 1088.18   119.5  1068.9
     129 1062.93   138.6 1058.19   148.1 1055.01   157.7 1052.79   162.3 1052.37
   167.3 1051.91   172.3 1052.68   176.8 1053.37   186.4  1056.5   195.9  1059.7
   205.5 1062.42   215.1 1064.89   225.1 1067.31   235.1 1069.55   255.1 1073.69
   275.1 1077.63   285.2 1079.45   295.2 1081.05   305.2 1082.25
#Mann= 3 , 0 , 0
       0     .06       0   162.3    .045       0   172.3     .06       0
Bank Sta=162.3,172.3
XS Rating Curve= 0 ,0
Exp/Cntr=0.3,0.1