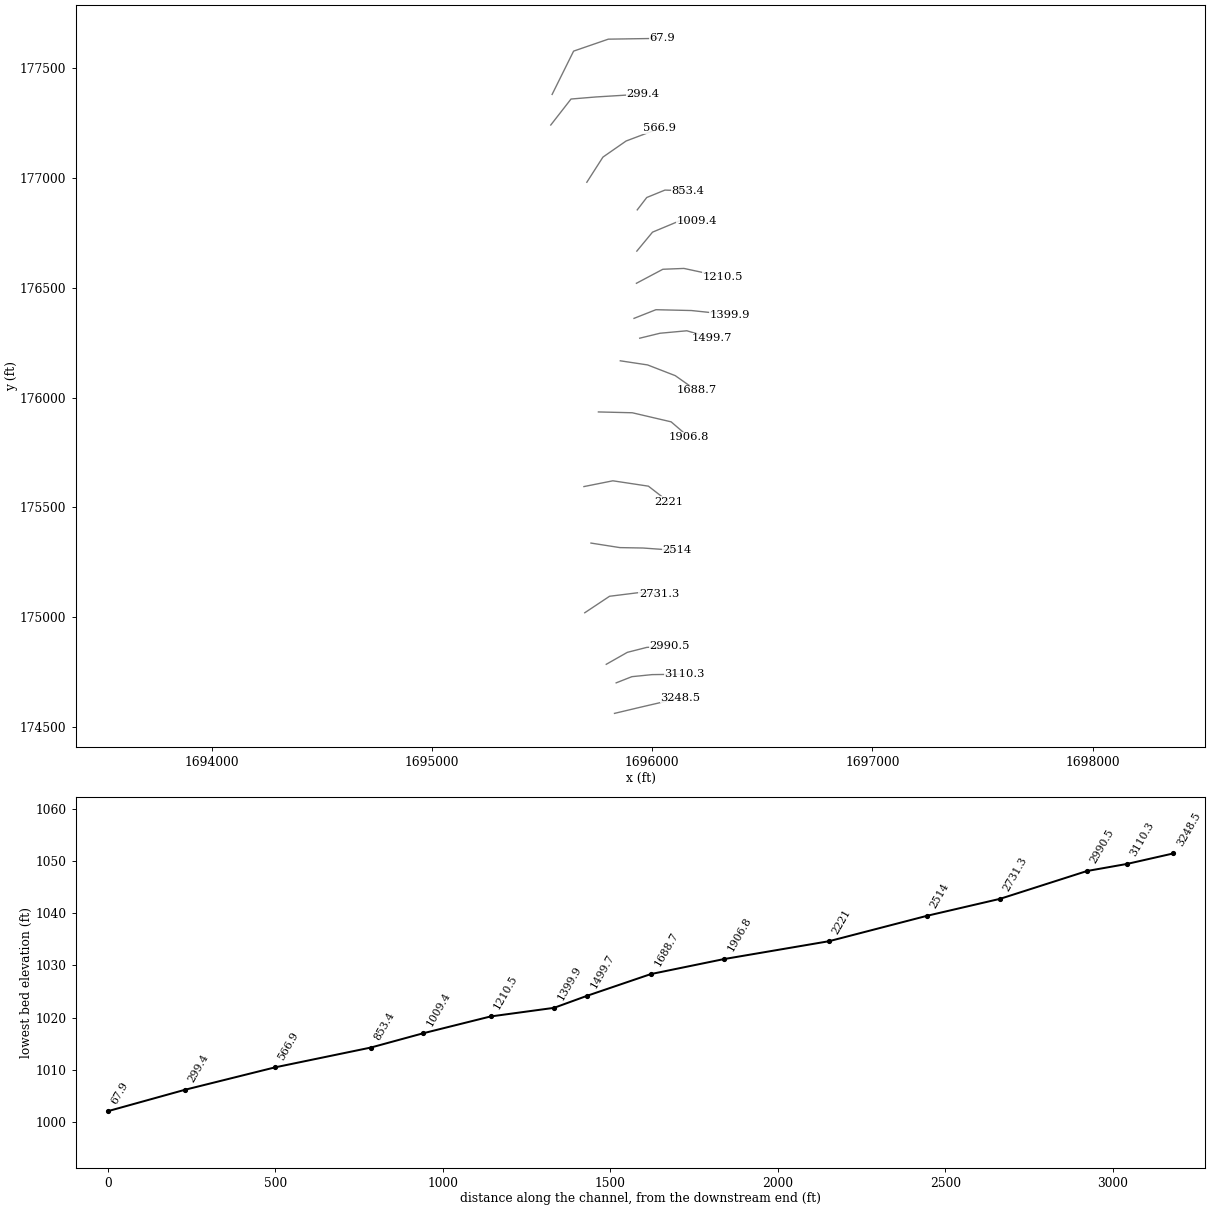
HEC-RAS study Mud Fork.prj: Mud Fork

--- Mud Fork.g01 (geometry) --- (continued)

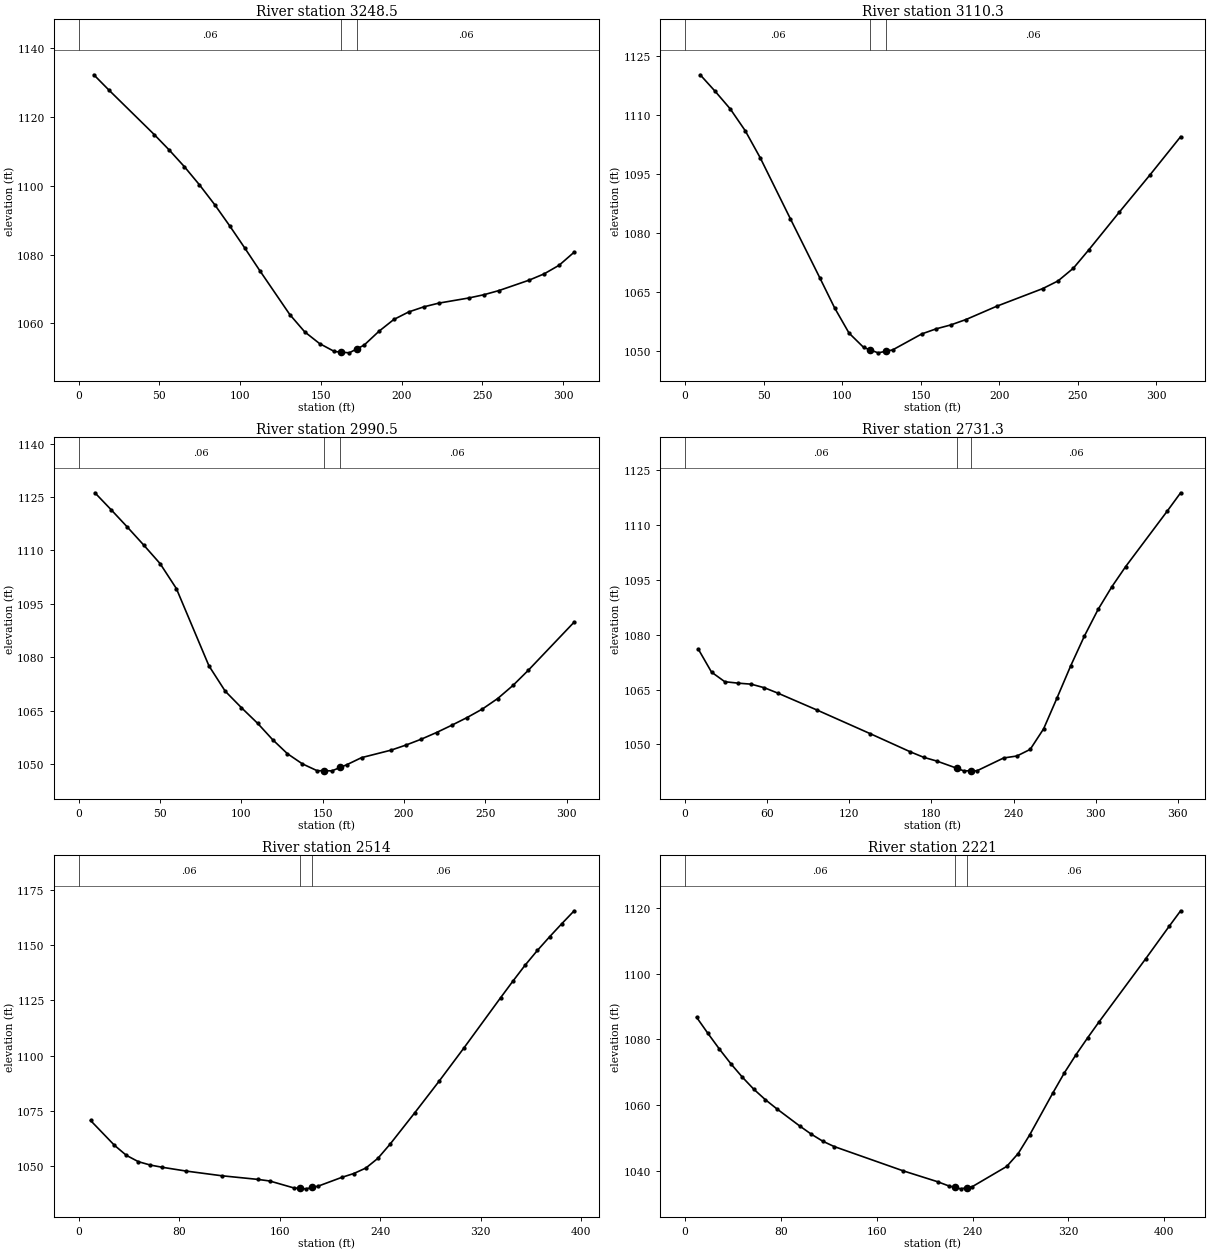
Type RM Length L Ch R = 1 ,3248.5  ,140.8,138.2,135.7
XS GIS Cut Line= 4
     1695828.327      174562.086     1695946.593      174590.244
     1696027.314      174609.017     1696126.808      174633.421
#Sta/Elev= 30
     9.4 1132.31    18.7 1127.89    46.8 1114.94    56.1 1110.43    65.5 1105.58
    74.8 1100.32    84.2 1094.58    93.5 1088.41   102.9 1081.92   112.2 1075.35
   130.8 1062.56     140 1057.55   149.2 1054.14   158.4 1051.83   162.6 1051.65
   167.6 1051.44   172.6 1052.66   176.8 1053.68     186 1057.71   195.2 1061.14
   204.4 1063.33   213.8 1064.82   223.1  1065.9   241.7  1067.4     251 1068.34
   260.3 1069.55     279 1072.58   288.3 1074.41   297.6 1076.92   306.9 1080.72
#Mann= 3 , 0 , 0
       0     .06       0   162.6    .045       0   172.6     .06       0
Bank Sta=162.6,172.6
XS Rating Curve= 0 ,0
Exp/Cntr=0.3,0.1

Type RM Length L Ch R = 1 ,3110.3  ,116.8,119.8,122.7
XS GIS Cut Line= 4
     1695835.836      174701.001     1695907.171       174729.16
     1695999.156      174738.546      1696145.58      174740.423
#Sta/Elev= 26
     9.6  1120.2    19.2 1115.97    28.8 1111.49    38.3 1105.96    47.9 1099.03
    67.1 1083.51    85.9 1068.44    95.2 1060.89   104.4 1054.46   113.7 1050.81
   117.9 1050.18   122.9 1049.43   127.9 1049.83   132.2 1050.18   150.7 1054.24
   159.9 1055.54   169.2 1056.53   178.9 1057.91   198.4 1061.28   227.7 1065.77
   237.5 1067.73   247.3 1070.98     257 1075.59   276.5 1085.22   296.1 1094.73
   315.6 1104.45
#Mann= 3 , 0 , 0
       0     .06       0   117.9    .045       0   127.9     .06       0
Bank Sta=117.9,127.9
XS Rating Curve= 0 ,0
Exp/Cntr=0.3,0.1

Type RM Length L Ch R = 1 ,2990.5  ,261.7,259.2,256.7
XS GIS Cut Line= 4
     1695790.782      174785.477     1695886.521      174839.917
     1695974.752      174862.444        1696078.      174868.076
#Sta/Elev= 30
      10 1126.19      20 1121.42      30 1116.53      40 1111.51    50.1 1106.28
    60.1 1099.26    80.1 1077.57    90.1 1070.45   100.1  1065.8   110.1 1061.39
   119.2 1056.85   128.3  1052.9   137.5 1050.04   146.6 1048.11   150.7 1048.09
   155.7 1048.07   160.7 1049.01   164.8 1049.78   173.9 1051.78   192.1 1053.89
   201.2 1055.31   210.6 1056.96     220 1058.84   229.4 1060.89   238.8 1063.05
   248.2 1065.44   257.6 1068.39     267 1072.07   276.4 1076.32   304.6 1089.86
#Mann= 3 , 0 , 0
       0     .06       0   150.7    .045       0   160.7     .06       0
Bank Sta=150.7,160.7
XS Rating Curve= 0 ,0
Exp/Cntr=0.3,0.1

Type RM Length L Ch R = 1 ,2731.3  ,220.1,217.4,214.6
XS GIS Cut Line= 4
     1695693.166      175020.132       1695805.8      175095.221
     1695940.961      175112.116     1696031.069      175104.607
#Sta/Elev= 28
     9.7 1076.01    19.3 1069.76      29 1067.13    38.7 1066.74    48.3 1066.46
      58 1065.47    67.7 1064.02    96.7 1059.33   135.4 1052.89   164.6 1047.94
   174.3 1046.45     184 1045.41   198.5 1043.46   203.5 1042.75   208.5 1042.76
   213.2 1042.76   232.7 1046.27   242.4 1046.81   252.1 1048.62   261.9 1054.24
   271.6 1062.61   281.6  1071.4   291.7 1079.63   301.7 1086.91   311.8 1093.14
   321.8 1098.61     352  1113.7     362 1118.82
#Mann= 3 , 0 , 0
       0     .06       0   198.5    .045       0   208.5     .06       0
Bank Sta=198.5,208.5
XS Rating Curve= 0 ,0
Exp/Cntr=0.3,0.1

Type RM Length L Ch R = 1 ,2514    ,295.7,292.9,290.1
XS GIS Cut Line= 4
     1695721.324      175337.385     1695852.731      175316.736
     1695957.856      175314.858     1696113.667      175303.595
#Sta/Elev= 30
     9.5 1070.53    28.5 1059.27      38 1054.71    47.5 1051.85      57 1050.31
    66.5  1049.3    85.5 1047.58     114 1045.44   142.6  1043.8   152.1 1043.07
   171.3 1039.92   175.8 1039.73   180.8 1039.51   185.8 1040.12   190.4 1040.68
   209.5 1044.73     219 1046.46   228.6 1048.95   238.2 1053.37   247.9  1059.8
   267.5 1074.01     287 1088.44   306.5 1103.33   335.8 1126.21   345.6 1133.74
   355.3 1140.97   365.1 1147.69   374.9 1153.93   384.6 1159.87   394.4  1165.7
#Mann= 3 , 0 , 0
       0     .06       0   175.8    .045       0   185.8     .06       0
Bank Sta=175.8,185.8
XS Rating Curve= 0 ,0
Exp/Cntr=0.3,0.1

Type RM Length L Ch R = 1 ,2221    ,315.8,314.2,312.6
XS GIS Cut Line= 4
     1695689.411      175594.567     1695820.818      175620.848
     1695982.261      175596.444     1696074.245      175525.109
#Sta/Elev= 30
     9.6 1086.73    19.1 1081.82    28.7 1077.05    38.3 1072.58    47.9 1068.51
    57.4 1064.87      67 1061.71    76.6 1058.93    95.7 1053.72   105.3 1051.25
   114.9 1049.11   124.4 1047.49     182 1040.11   210.8  1036.8   220.4 1035.49
   225.1 1035.08   230.1 1034.64   235.1 1034.98   239.7 1035.29   268.5 1041.44
   278.1 1045.37   287.7 1051.03     307 1063.74   316.7  1069.9   326.4  1075.4
   336.1 1080.52   345.8 1085.45   384.6 1104.54     404  1114.3   413.7 1119.07
#Mann= 3 , 0 , 0
       0     .06       0   225.1    .045       0   235.1     .06       0
Bank Sta=225.1,235.1
XS Rating Curve= 0 ,0
Exp/Cntr=0.3,0.1

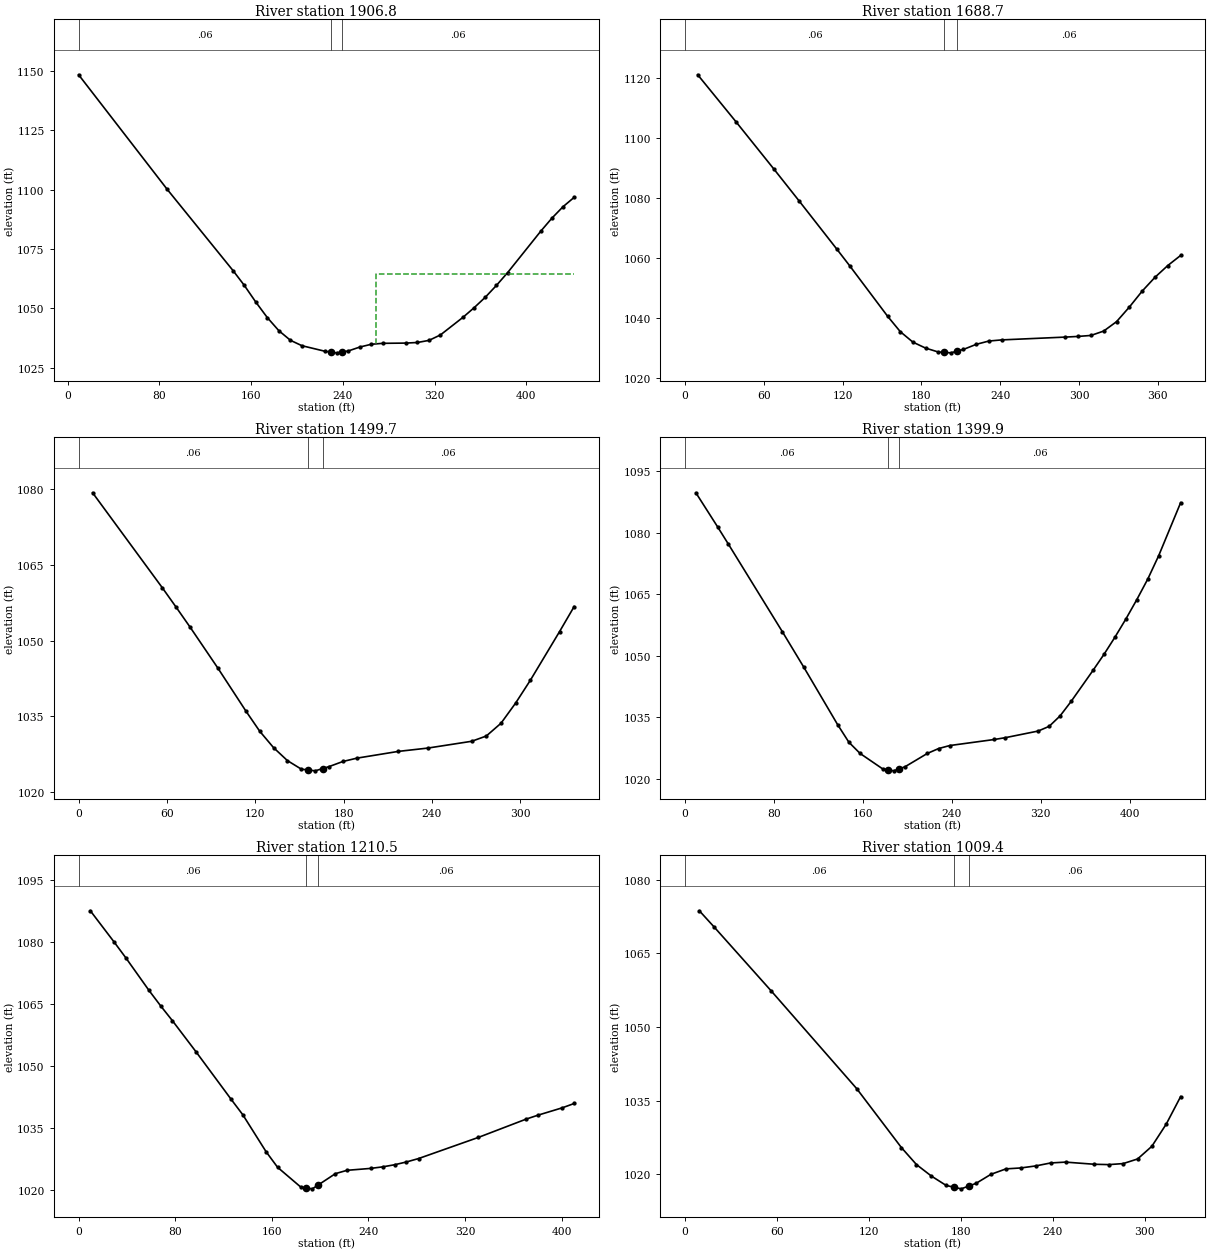
Type RM Length L Ch R = 1 ,1906.8  ,220.9,218.1,215.3
XS GIS Cut Line= 4
     1695755.115      175934.347     1695909.048      175930.592
     1696085.509      175889.293      1696166.23      175819.835
#Sta/Elev= 30
     9.6 1148.41    86.6 1100.26   144.4 1065.78     154 1059.69     164 1052.67
   174.1 1046.08   184.2 1040.54   194.3 1036.49   204.3 1034.22   224.5 1031.86
   229.5 1031.53   234.5 1031.21   239.5 1031.59   244.6 1031.98   254.7 1033.64
   264.7 1034.81   274.8 1035.22   294.9 1035.32     305 1035.57   315.1 1036.46
   325.1 1038.76   344.9 1046.24   354.6 1050.29   364.3 1054.69   373.9 1059.62
   383.6 1064.98   412.7 1082.56   422.3 1087.98     432 1092.81   441.7 1096.75
#Mann= 3 , 0 , 0
     9.6     .06       0   229.5    .045       0   239.5     .06       0
#XS Ineff= 2 , 0
                           269.3         1064.43
Permanent Ineff=
       F       F
Bank Sta=229.5,239.5
XS Rating Curve= 0 ,0
Exp/Cntr=0.3,0.1

Type RM Length L Ch R = 1 ,1688.7  ,179.7,189,198.3
XS GIS Cut Line= 4
     1695854.608      176167.124     1695978.506      176148.352
     1696104.281      176099.544      1696200.02      176031.963
#Sta/Elev= 28
     9.6 1121.03    38.6 1105.45    67.5 1089.67    86.8    1079   115.7 1062.83
   125.3 1057.39   154.2 1040.55   163.9 1035.39   173.5 1031.91   183.1 1029.93
   192.8 1028.62   197.4 1028.49   202.4 1028.34   207.4 1028.94     212 1029.48
   221.7 1031.17   231.3 1032.27     241 1032.65   289.5 1033.59   299.3 1033.81
   309.1 1034.14   318.8  1035.6   328.6 1038.74   338.4 1043.63   348.1 1048.91
   357.9 1053.54   367.6 1057.44   377.4 1060.81
#Mann= 3 , 0 , 0
       0     .06       0   197.4    .045       0   207.4     .06       0
Bank Sta=197.4,207.4
XS Rating Curve= 0 ,0
Exp/Cntr=0.3,0.1

Type RM Length L Ch R = 1 ,1499.7  ,102.1,99.8,97.5
XS GIS Cut Line= 4
     1695942.839      176270.036     1696034.823      176292.563
     1696156.844      176303.826     1696271.355      176270.036
#Sta/Elev= 25
     9.5 1079.24    56.8 1060.46    66.3 1056.57    75.8 1052.61    94.7 1044.49
   113.6 1036.05     123 1032.05   132.4  1028.8   141.8 1026.24   151.3 1024.54
   155.7 1024.39   160.7 1024.21   165.7 1024.66   170.1 1025.05   179.5 1026.06
     189 1026.72   217.2 1028.06   237.1 1028.71     267 1030.06   276.9  1031.1
   286.9 1033.63   296.8 1037.61   306.8 1042.12   326.7 1051.78   336.6 1056.73
#Mann= 3 , 0 , 0
       0     .06       0   155.7    .045       0   165.7     .06       0
Bank Sta=155.7,165.7
XS Rating Curve= 0 ,0
Exp/Cntr=0.3,0.1

Type RM Length L Ch R = 1 ,1399.9  ,188.1,189.4,190.7
XS GIS Cut Line= 4
     1695916.927      176360.321     1696016.421      176399.743
     1696177.864      176395.988     1696354.324      176377.216
#Sta/Elev= 30
     9.7 1089.71    29.2 1081.42    38.9 1077.21    87.6 1055.79     107 1047.09
   137.3 1033.14   147.4 1028.86   157.5 1026.12   177.7 1022.38   182.8 1022.13
   187.8 1021.88   192.8 1022.37   197.9 1022.87     218 1026.12   228.1 1027.31
   238.2 1028.05   278.4 1029.53   288.2 1029.97   317.8 1031.59   327.7 1032.74
   337.5 1035.28   347.4  1038.8   367.1 1046.37     377 1050.29   386.8 1054.45
   396.7 1058.91   406.5 1063.62   416.4 1068.65   426.2 1074.34     446 1087.29
#Mann= 3 , 0 , 0
       0     .06       0   182.8    .045       0   192.8     .06       0
Bank Sta=182.8,192.8
XS Rating Curve= 0 ,0
Exp/Cntr=0.3,0.1

Type RM Length L Ch R = 1 ,1210.5  ,194,201.2,208.3
XS GIS Cut Line= 4
     1695927.821      176520.045     1696047.964      176583.871
     1696143.703      176587.626     1696318.286      176550.081
#Sta/Elev= 27
     9.7 1087.47    29.2 1079.99    38.9 1076.17    58.3  1068.2      68 1064.45
    77.7 1060.88    97.2 1053.38   126.3 1041.88     136 1038.13   155.2 1029.23
   164.8 1025.43     184 1020.65   188.5 1020.45   193.5 1020.23   198.5 1021.18
   212.7 1023.91   222.3 1024.71   241.8 1025.17   251.7 1025.54   261.6 1026.05
   271.5 1026.73   281.5 1027.55   331.1 1032.67   370.7  1037.1   380.7 1038.07
   400.5 1039.82   410.4 1040.87
#Mann= 3 , 0 , 0
       0     .06       0   188.5    .045       0   198.5     .06       0
Bank Sta=188.5,198.5
XS Rating Curve= 0 ,0
Exp/Cntr=0.3,0.1

Type RM Length L Ch R = 1 ,1009.4  ,156.1,156,155.8
XS GIS Cut Line= 4
     1695929.698       176666.47     1696001.033      176752.823
     1696126.808      176805.386     1696201.897      176805.386
#Sta/Elev= 25
     9.3 1073.71    18.7 1070.49      56 1057.44     112 1037.44   141.2 1025.41
     151 1021.96   160.7 1019.62   170.4  1017.7   175.2 1017.36   180.2 1017.01
   185.2 1017.59   189.9 1018.13   199.6 1019.97   209.4 1021.08   219.1 1021.27
   228.8 1021.68   238.6 1022.29   248.3 1022.46   267.1 1022.02   276.5 1021.95
   285.9 1022.16   295.3  1023.1   304.6 1025.68     314 1030.21   323.4 1035.82
#Mann= 3 , 0 , 0
       0     .06       0   175.2    .045       0   185.2     .06       0
Bank Sta=175.2,185.2
XS Rating Curve= 0 ,0
Exp/Cntr=0.3,0.1

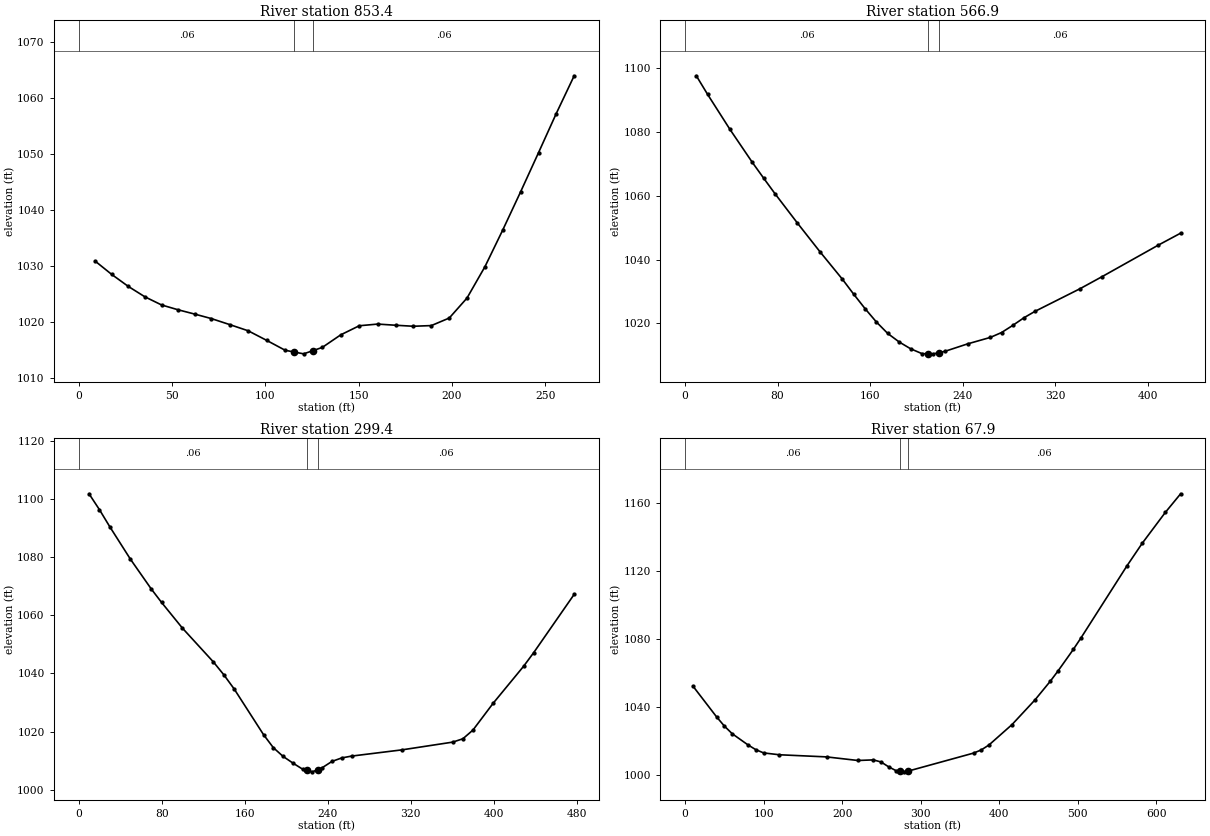
Type RM Length L Ch R = 1 ,853.4   ,282.2,286.5,290.9
XS GIS Cut Line= 4
     1695931.575      176854.194     1695974.752      176910.511
      1696057.35      176944.301     1696162.475      176940.547
#Sta/Elev= 30
     8.9 1030.84    17.7 1028.48    26.6 1026.33    35.5 1024.47    44.4 1023.02
    53.2 1022.16    62.1 1021.39      71 1020.59    80.9 1019.51    90.8  1018.4
   100.7 1016.69   110.6 1014.92   115.5  1014.6   120.5 1014.28   125.5 1014.85
   130.5 1015.43   140.4 1017.68   150.3  1019.3   160.2  1019.6   169.8 1019.39
   179.3 1019.21   188.9 1019.33   198.5 1020.68     208 1024.25   217.6 1029.85
   227.1 1036.38   236.7 1043.23   246.3 1050.23   255.8 1057.23   265.4 1063.98
#Mann= 3 , 0 , 0
       0     .06       0   115.5    .045       0   125.5     .06       0
Bank Sta=115.5,125.5
XS Rating Curve= 0 ,0
Exp/Cntr=0.3,0.1

Type RM Length L Ch R = 1 ,566.9   ,278.1,267.5,256.8
XS GIS Cut Line= 4
     1695702.552      176979.969     1695775.764       177094.48
      1695880.89      177167.692     1696034.823      177225.887
#Sta/Elev= 30
     9.7 1097.69    19.4 1091.89    38.8 1080.87    58.2  1070.5      68 1065.55
    77.7 1060.73    97.1 1051.52   116.5 1042.57   135.9 1033.95   145.8  1029.2
   155.6 1024.68   165.5 1020.45   175.3 1016.86   185.2 1014.19     195 1012.08
   204.9 1010.54   209.8 1010.51   214.8 1010.48   219.8 1010.87   224.6 1011.25
   244.3  1013.6     264 1015.63   273.7 1017.16   283.4  1019.4   293.1  1021.8
   302.7 1023.82   341.5 1030.89   360.8 1034.72   409.2 1044.56   428.6 1048.33
#Mann= 3 , 0 , 0
       0     .06       0   209.8    .045       0   219.8     .06       0
Bank Sta=209.8,219.8
XS Rating Curve= 0 ,0
Exp/Cntr=0.3,0.1

Type RM Length L Ch R = 1 ,299.4   ,226.3,231.5,236.7
XS GIS Cut Line= 4
     1695538.783      177240.561     1695630.767      177358.827
     1695743.402      177368.214     1695957.407      177381.354
#Sta/Elev= 30
      10 1101.75      20 1096.32      30 1090.43    49.9 1079.27    69.9 1069.07
    79.9 1064.41    99.9 1055.62   129.8 1043.97   139.8 1039.58   149.8 1034.69
   178.1 1018.99   187.5 1014.53   196.9 1011.52   206.3 1009.24   215.8 1007.11
   220.2 1006.69   225.2 1006.21   230.2 1006.96   234.6 1007.62     244 1009.79
   253.4 1010.99   262.9 1011.62   311.6 1013.77   360.3 1016.42   370.1 1017.57
   379.8 1020.56   399.3 1029.79   428.5 1042.44   438.3 1047.16   477.3 1067.19
#Mann= 3 , 0 , 0
       0     .06       0   220.2    .045       0   230.2     .06       0
Bank Sta=220.2,230.2
XS Rating Curve= 0 ,0
Exp/Cntr=0.3,0.1

Type RM Length L Ch R = 1 ,67.9    ,73.5,67.9,62.3
XS GIS Cut Line= 4
     1695544.864       177379.82      1695642.48       177576.93
     1695800.168       177631.37     1696044.209      177635.125
#Sta/Elev= 30
      10 1052.44      40 1034.42      50 1028.97      60 1024.47      80 1017.93
      90 1015.11     100  1013.2     120 1012.12     180 1010.87     220 1008.76
   239.6 1009.11   249.4 1007.89   259.2 1005.01     269 1002.67   273.8 1002.39
   278.8 1002.09   283.8 1002.51   367.2  1013.1     377 1014.96   386.8 1017.86
   416.1 1029.82   445.4 1044.35   464.9 1055.33   474.6 1061.27   494.2    1074
   503.9 1080.73   562.5 1123.11     582 1136.41   611.3 1154.47   630.8 1165.42
#Mann= 3 , 0 , 0
       0     .06       0   273.8    .045       0   283.8     .06       0
Bank Sta=273.8,283.8
XS Rating Curve= 0 ,0
Exp/Cntr=0.3,0.1

Chan Stop Cuts=-1
Use User Specified Reach Order=0